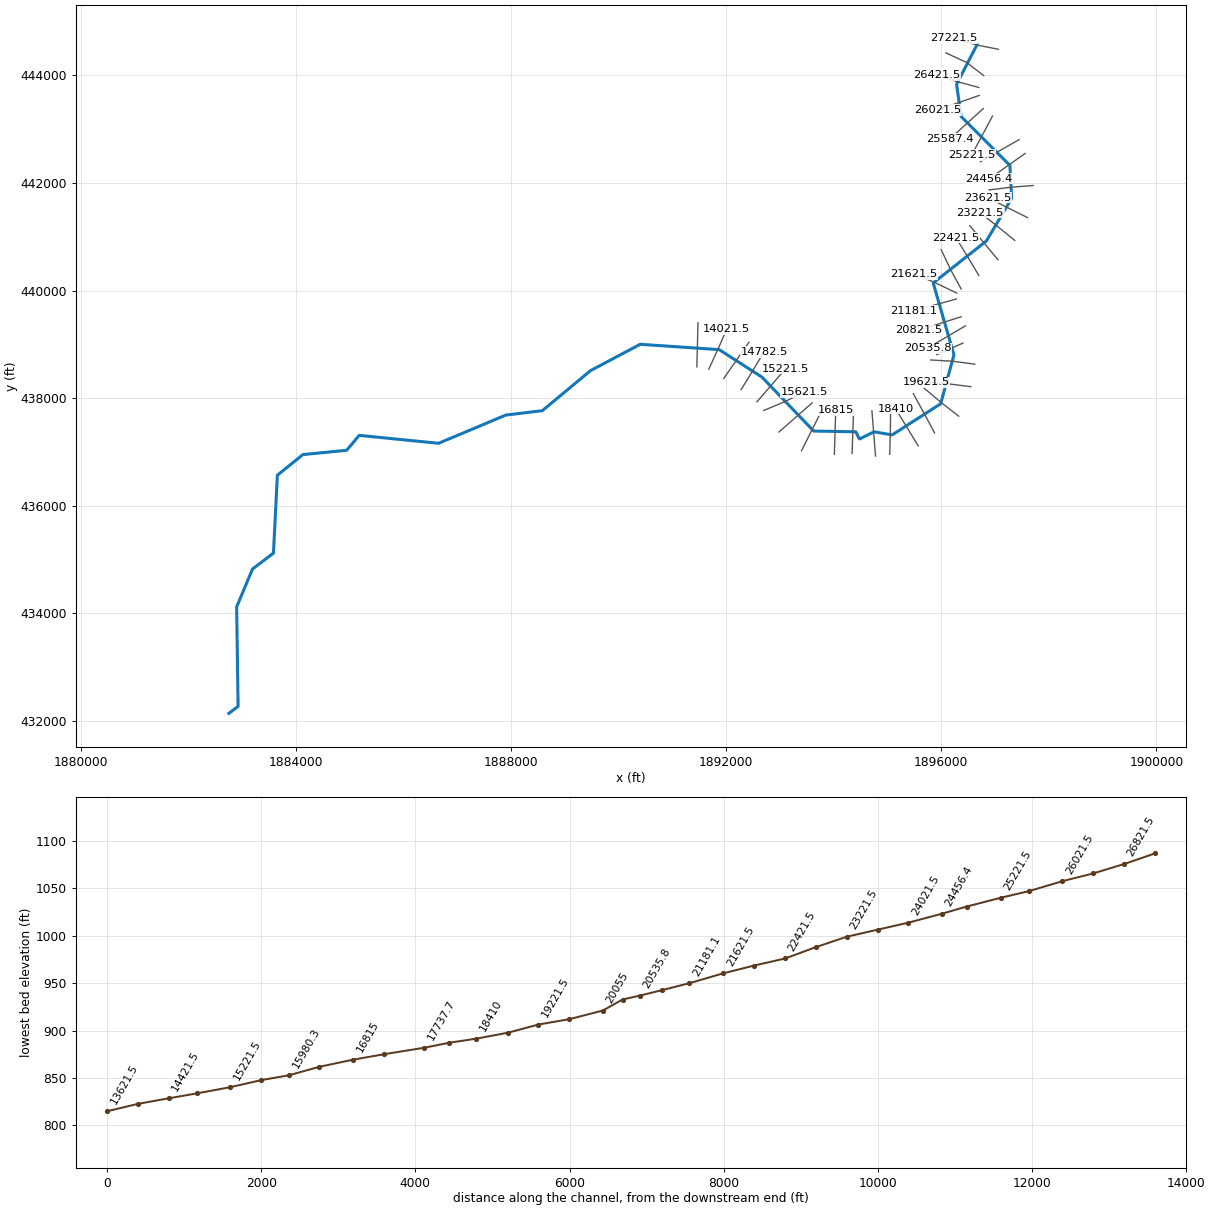
--- SmithersCk.prj (project) ---

Proj Title=SmithersCk
Current Plan=p01
Default Exp/Contr=0,0
English Units
Geom File=g01
Flow File=f01
Plan File=p01
BEGIN DESCRIPTION:
END DESCRIPTION:
DSS Export Rating Curves= 0
DSS Export Rating Curve Sorted= 0
DSS Export Volume Flow Curves= 0
DXF OffsetX= 0
DXF OffsetY= 0
DXF ScaleX= 0
DXF ScaleY= 0

--- SmithersCk.p01 (plan) ---

Plan Title=Floodplain
Program Version=4.00
Geom File=g01
Flow File=f01
K Sum by GR=0
Std Step Tol=0.01
Critical Tol=0.01
Num of Std Step Trials=20
Max Error Tol=0.3
Flow Tol Ratio=0.001
Split Flow NTrial=30
Split Flow Tol=0.02
Split Flow Ratio=0.02
Log Output Level=0
Friction Slope Method=1
Unsteady Friction Slope Method=2
Unsteady Bridges Friction Slope Method=1
Global Log Level=0
CheckData=False
Run HTab=0
Run UNet=0
Run PostProcess=0
UNET Theta=0
UNET Theta Warmup=0
UNET ZTol=0
UNET ZSATol=0
UNET MxIter=0
UNET MaxInSteps=0
UNET DtIC=0
UNET DtMin=0
UNET MaxCRTS=0
UNET WFStab=0
UNET SFStab=0
UNET WFX=0
UNET SFX=0
UNET DSS MLevel=0
UNET DZMax Abort=0
UNET Convert EG Bridges=0
UNET Use Existing IB Tables=0
UNET Froude Limit=0
UNET Froude Power=0
Write IC File=0
Echo Input=False
Echo Output=False
Write Detailed=0

--- SmithersCk.f01 (steady flow) ---

Flow Title=NFF Regression Equation
Program Version=4.10
Number of Profiles= 1
Profile Names=P100yr
River Rch & RM=SmithersCk,Main            ,27221.5
979.3314
River Rch & RM=SmithersCk,Main            ,26021.5
993.5687
River Rch & RM=SmithersCk,Main            ,23621.5
1101.452
River Rch & RM=SmithersCk,Main            ,20055
1181.064
River Rch & RM=SmithersCk,Main            ,19621.5
1333.032
River Rch & RM=SmithersCk,Main            ,18828.1
1342.861
River Rch & RM=SmithersCk,Main            ,18410
1689.966
River Rch & RM=SmithersCk,Main            ,17737.7
1737.921
River Rch & RM=SmithersCk,Main            ,14782.5
1927.858
River Rch & RM=SmithersCk,Main            ,12494.9
2065.536
River Rch & RM=SmithersCk,Main            ,9621.9
2233.559
River Rch & RM=SmithersCk,Main            ,4883.7
2480.231
River Rch & RM=SmithersCk,Main            ,4606.2
3223.665
River Rch & RM=SmithersCk,Main            ,444.7
3361.952
Boundary for River Rch & Prof#=SmithersCk,Main            , 1
Up Type= 0
Dn Type= 1
Dn Known WS=651.2
DSS Import GetInterval= 0
DSS Import GetPeak= 0
DSS Import FillOption= 0

--- SmithersCk.g01 (geometry) ---

Geom Title=USGS 3m DEM
Program Version=4.10

River Reach=SmithersCk      ,Main
Reach XY= 30
     1896665.098      444573.987     1896283.451      443835.298
     1896368.402        443235.2     1897274.473      442327.459
     1897307.459      441714.612     1896836.973      440921.209
     1895848.581      440140.965     1896234.542       438804.89
     1895988.015      437895.168     1895085.385      437316.705
     1894750.167      437374.334     1894477.598      437240.653
      1894410.83      437374.334     1893626.904      437388.223
     1892665.098      438391.695     1891869.959      438902.112
     1890402.945       439001.07      1889481.07      438513.223
     1888581.765      437766.695     1887902.945      437685.098
     1886654.877       437160.91     1885178.167      437307.709
     1884945.342      437031.022     1884132.112      436950.723
     1883656.951      436567.671     1883584.371      435119.257
     1883194.928       434823.47     1882899.912      434118.886
     1882926.844      432270.431      1882755.36      432139.638

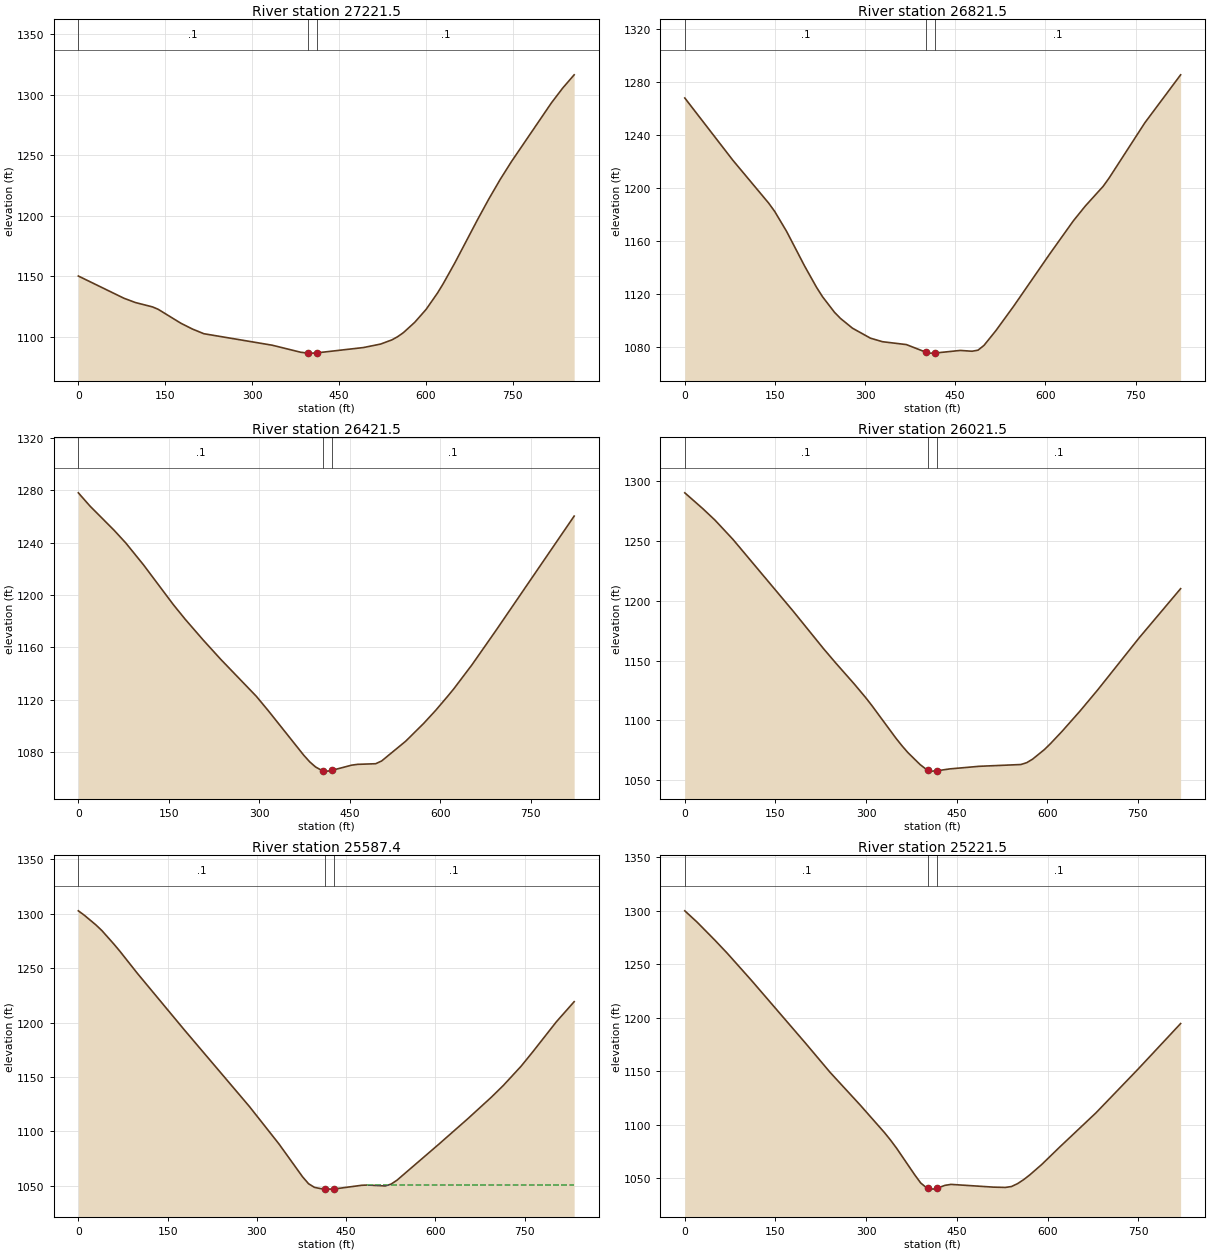
Type RM Length L Ch R = 1 ,27221.5 ,409.9,399.9,397
XS GIS Cut Line= 3
     1897062.153      444485.362     1896666.289      444564.058
     1896231.863      444689.187
#Sta/Elev= 30
       0 1150.29    78.8 1131.92    98.4 1128.41     128 1124.79   137.8 1122.81
   177.2 1111.24   196.9 1106.52   216.6 1102.66   334.7 1093.16   383.9 1087.34
   396.1 1086.67   403.6 1086.63   411.1 1086.81   492.1 1091.24   521.6  1094.1
   541.2 1097.57     551 1100.17   560.9  1103.5   580.5 1112.03   600.2 1122.74
   619.8  1136.2   629.6 1143.86   649.3 1160.69   688.6 1196.49   708.3 1213.76
   727.9 1229.89   747.6 1244.83   816.4 1293.18     836 1305.49   855.7 1316.38
#Mann= 3 , 0 , 0
       0      .1       0   396.1    .045       0   411.1      .1       0
Bank Sta=396.1,411.1
XS Rating Curve= 0 ,0
Exp/Cntr=0.3,0.1

Type RM Length L Ch R = 1 ,26821.5 ,391.3,400,402.7
XS GIS Cut Line= 3
      1896788.45      443996.531     1896463.365       444244.06
     1896085.242       444418.54
#Sta/Elev= 30
       0 1268.17    79.7  1221.3   139.5 1188.79   149.5 1182.56   169.4  1167.4
   199.3 1141.28   219.2 1125.16   229.2 1118.04   249.1 1106.28   259.1 1101.64
     279 1094.28   308.9 1086.75   328.9 1084.08   368.7  1081.9   401.1 1076.16
   408.6 1075.45   416.1  1075.5   458.2 1077.48     478 1076.88   487.9 1077.69
   497.8 1081.28   517.7 1092.49   547.4 1111.03   606.9 1150.16   646.6 1175.43
   666.4 1186.56   696.1 1201.44     706 1207.72   765.5 1249.46     825 1285.67
#Mann= 3 , 0 , 0
       0      .1       0   401.1    .045       0   416.1      .1       0
Bank Sta=401.1,416.1
XS Rating Curve= 0 ,0
Exp/Cntr=0.3,0.1

Type RM Length L Ch R = 1 ,26421.5 ,386.2,399.9,414.4
XS GIS Cut Line= 3
     1896697.988      443775.296     1896299.281      443883.738
      1895909.41      444006.855
#Sta/Elev= 30
       0 1277.94    19.7 1267.65      59 1249.52    78.7 1239.66   108.2 1222.89
   157.4 1192.68   177.1  1181.5   206.6 1165.82   236.1 1150.88   295.1 1122.66
   314.8 1111.75   373.8 1077.65   383.7  1072.6   393.5 1068.67   403.4 1066.17
   405.7 1066.03   413.2 1065.56   420.7 1066.19   453.1 1070.11     463 1070.73
     493 1071.21   502.9 1073.33   542.8 1088.43   572.7 1102.06   592.7 1112.07
   612.6 1122.84   622.6 1128.45   652.5 1146.65   692.4 1172.92     822 1260.18
#Mann= 3 , 0 , 0
       0      .1       0   405.7    .045       0   420.7      .1       0
Bank Sta=405.7,420.7
XS Rating Curve= 0 ,0
Exp/Cntr=0.3,0.1

Type RM Length L Ch R = 1 ,26021.5 ,425.1,434.1,443.1
XS GIS Cut Line= 3
     1896705.573      443628.199     1896319.382      443492.848
     1895931.035      443357.146
#Sta/Elev= 30
       0 1290.43    29.9 1277.13    49.9 1267.61    79.8 1251.39   179.7 1191.14
   229.6 1159.95   249.5 1148.12   279.5 1130.94   299.4 1118.95   309.4 1112.46
   349.3 1085.07   359.3 1078.72   369.3 1072.89   389.3 1062.96   399.2 1059.06
   401.7 1058.64   409.2  1057.4   416.7 1057.63   438.6 1059.27   487.6 1061.45
   556.1 1062.92   565.9 1064.48   575.7 1067.46   595.3 1075.52   605.1 1080.37
   624.7  1090.9   654.1 1107.71   683.5  1125.5     752 1169.03   820.6  1210.2
#Mann= 3 , 0 , 0
       0      .1       0   401.7    .045       0   416.7      .1       0
Bank Sta=401.7,416.7
XS Rating Curve= 0 ,0
Exp/Cntr=0.3,0.1

Type RM Length L Ch R = 1 ,25587.4 ,357.8,365.7,373.5
XS GIS Cut Line= 2
     1896779.951      443383.148     1896162.265      442824.259
#Sta/Elev= 30
       0 1302.65     9.9 1298.67    29.8 1289.58    39.7 1284.42    59.5 1272.24
    69.4 1265.81    99.2 1245.19   178.5 1192.98   287.6  1122.7   337.2 1088.32
   376.8 1058.16   386.8 1051.85   396.7 1048.51   406.6 1047.41   414.9 1047.01
   426.4 1046.89   429.9 1047.03     476 1050.42   485.9 1050.65   515.7 1049.82
   525.6 1051.53   535.5 1055.16   604.9 1087.81   654.5 1111.68   694.2 1131.53
     714 1142.15   743.8 1159.81   763.6 1173.14   803.2 1200.72     833 1219.14
#Mann= 3 , 0 , 0
       0      .1       0   414.9    .045       0   429.9      .1       0
#XS Ineff= 2 , 0
                          485.74         1050.65
Permanent Ineff=
       F       F
Bank Sta=414.9,429.9
XS Rating Curve= 0 ,0
Exp/Cntr=0.3,0.1

Type RM Length L Ch R = 1 ,25221.5 ,454.8,441.9,429.2
XS GIS Cut Line= 3
     1896951.286      443244.167     1896758.848      442881.752
     1896564.108      442521.176
#Sta/Elev= 30
       0 1299.93      20 1289.56      50 1272.37    70.1 1260.38   110.1 1235.05
   200.2 1175.93   240.2  1149.1   290.2 1118.41   330.3 1092.72   340.3 1085.73
   350.3 1078.14   380.3 1053.29   390.3  1045.6   400.3 1041.02   402.8 1040.74
   410.3 1039.92   417.8  1040.9   430.3 1043.44   440.3 1044.35   510.3 1041.79
   530.3 1041.51   540.3 1042.35   550.3 1045.01   560.3 1048.71   570.3 1053.08
   590.2 1062.85   620.2 1079.28   680.2 1111.26   750.2 1152.33   820.1 1194.61
#Mann= 3 , 0 , 0
       0      .1       0   402.8    .045       0   417.8      .1       0
Bank Sta=402.8,417.8
XS Rating Curve= 0 ,0
Exp/Cntr=0.3,0.1

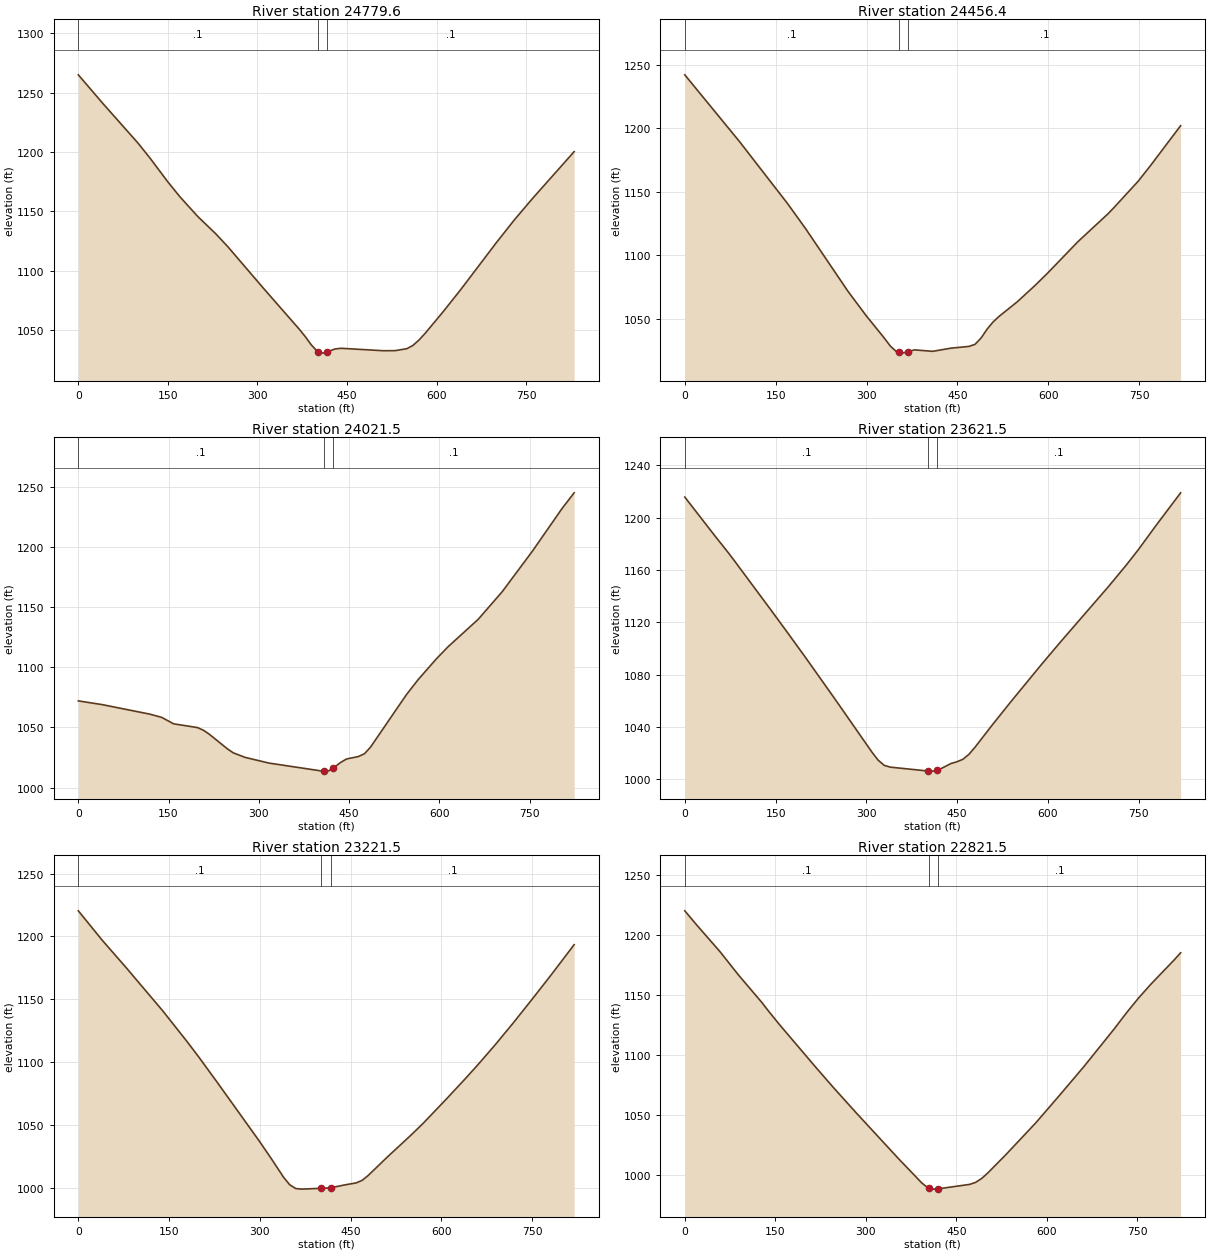
Type RM Length L Ch R = 1 ,24779.6 ,321,323.2,325.5
XS GIS Cut Line= 2
     1897446.474       442806.15     1896724.686      442395.761
#Sta/Elev= 30
       0 1264.88      40 1241.41     100 1207.39     120 1194.83     150 1174.72
   170.1 1162.27   200.1  1145.6   230.1 1131.13   250.1 1120.38   310.1  1085.2
   370.1 1050.73   380.1 1044.53   390.1 1037.62   400.8 1031.81   410.2 1030.67
   415.8 1031.59   430.2 1034.19   440.2 1034.74   510.2  1032.7   530.2 1032.74
   550.2 1034.41   560.2 1037.12   570.2 1041.56   580.2 1046.99   610.2 1065.08
   640.2 1084.03   700.2 1123.77   730.3  1142.9   760.3 1160.65   830.3 1200.24
#Mann= 3 , 0 , 0
       0      .1       0   400.8    .045       0   415.8      .1       0
Bank Sta=400.8,415.8
XS Rating Curve= 0 ,0
Exp/Cntr=0.3,0.1

Type RM Length L Ch R = 1 ,24456.4 ,446.9,434.8,423.6
XS GIS Cut Line= 2
     1897558.516      442549.136     1896889.862      442077.386
#Sta/Elev= 30
       0 1242.21    89.8 1189.94   169.6 1140.84   199.6 1120.94   269.4  1071.7
   299.4 1052.53   329.3  1034.9   339.3 1028.59   349.3 1024.28   353.3  1023.8
   359.3 1023.08   368.3 1024.33   379.2 1025.63   409.2  1024.5   439.1 1026.98
     469 1028.37     479 1029.99     489    1035     499    1042     509 1047.74
   518.9  1052.1   548.9 1063.58   578.8 1076.72   598.8  1086.1   648.7 1110.79
   698.6 1132.85   708.5 1137.77   748.5 1158.58   768.4 1170.62   818.3 1202.15
#Mann= 3 , 0 , 0
       0      .1       0   353.3    .045       0   368.3      .1       0
Bank Sta=353.3,368.3
XS Rating Curve= 0 ,0
Exp/Cntr=0.3,0.1

Type RM Length L Ch R = 1 ,24021.5 ,412.2,400,386.7
XS GIS Cut Line= 3
      1897707.51      441953.012     1897292.927      441921.146
     1896887.693      441870.494
#Sta/Elev= 30
       0    1072    39.6 1068.89   118.8 1060.98   138.6 1058.29   158.4 1052.94
     198 1049.82   207.9 1047.62   217.8 1044.27   247.5 1032.27   257.4 1028.87
   277.2 1025.06   316.8 1020.34   405.9 1013.65   408.3 1013.69   415.8 1013.83
   423.3 1015.95   435.7 1020.76   445.7 1023.71   465.6 1025.77   475.6 1028.09
   485.5 1033.42   545.3  1077.1   565.2 1089.84   595.1 1106.87     615 1117.15
   664.8 1139.78   704.7 1162.73   754.5 1196.12   804.3 1231.92   824.2 1244.79
#Mann= 3 , 0 , 0
       0      .1       0   408.3    .045       0   423.3      .1       0
Bank Sta=408.3,423.3
XS Rating Curve= 0 ,0
Exp/Cntr=0.3,0.1

Type RM Length L Ch R = 1 ,23621.5 ,404.8,399.9,395.6
XS GIS Cut Line= 3
     1897601.914      441356.602     1897235.646      441539.735
     1896869.377      441722.868
#Sta/Elev= 30
       0 1215.81    49.9 1186.04    69.9 1174.42    79.9 1168.37   139.8 1131.03
   169.8  1112.1   199.8 1092.92   249.7  1060.3   309.6 1020.49   319.6 1014.55
   329.6 1010.64   339.6 1009.31     402 1006.34   409.5 1006.27     417 1007.03
   419.5 1007.28   439.5 1012.06   449.4 1013.41   459.4 1015.31   469.4 1019.15
   479.4 1024.55   509.4 1042.47   539.3 1059.74   589.3 1087.89   619.2 1104.29
   699.2 1147.05   729.1 1163.73   749.1 1175.56     779 1194.48     819 1219.05
#Mann= 3 , 0 , 0
       0      .1       0     402    .045       0     417      .1       0
Bank Sta=402,417
XS Rating Curve= 0 ,0
Exp/Cntr=0.3,0.1

Type RM Length L Ch R = 1 ,23221.5 ,404.4,400,395
XS GIS Cut Line= 3
     1897364.301      440932.896     1897047.012      441191.465
     1896723.421      441443.512
#Sta/Elev= 30
       0 1220.37    39.9 1196.74    79.9 1174.67   139.8 1140.59   179.7  1116.3
   199.7 1103.59   229.6 1083.83   299.5  1036.8   319.5 1022.69   339.4 1008.17
   349.4 1002.27   359.4  999.29   369.4  998.82   401.8  999.49   416.8  999.81
   439.3 1002.09   459.3 1003.78   469.3 1005.84   479.3 1009.78   509.4 1023.78
   549.4 1041.64   569.4 1050.94   609.4 1071.11   639.4 1086.64   659.4 1097.28
   689.4 1113.95   719.4 1131.46   749.4 1149.61   779.5 1168.13   819.5 1193.42
#Mann= 3 , 0 , 0
       0      .1       0   401.8    .045       0   416.8      .1       0
Bank Sta=401.8,416.8
XS Rating Curve= 0 ,0
Exp/Cntr=0.3,0.1

Type RM Length L Ch R = 1 ,22821.5 ,403.5,399.9,396.8
XS GIS Cut Line= 3
     1897053.298      440572.747     1896789.647      440889.659
     1896530.038      441205.993
#Sta/Elev= 30
       0 1220.08    19.6 1208.35    58.9 1185.68    88.3 1166.94   127.6 1143.67
   137.4 1137.27     157 1125.09   215.9 1090.22   245.4 1073.13   284.6 1051.21
   353.4 1013.68   392.6  993.08   402.4  989.13   404.7  988.84   412.2  987.89
   419.7  988.12   472.1  991.86   482.1  993.57   492.1  996.88   502.1 1001.41
     532 1016.66   581.9 1043.39   621.8 1066.69   661.8 1090.47   711.7 1121.71
   731.6 1134.84   751.6 1147.21   771.6 1158.53   811.5 1179.48   821.5 1185.06
#Mann= 3 , 0 , 0
       0      .1       0   404.7    .045       0   419.7      .1       0
Bank Sta=404.7,419.7
XS Rating Curve= 0 ,0
Exp/Cntr=0.3,0.1

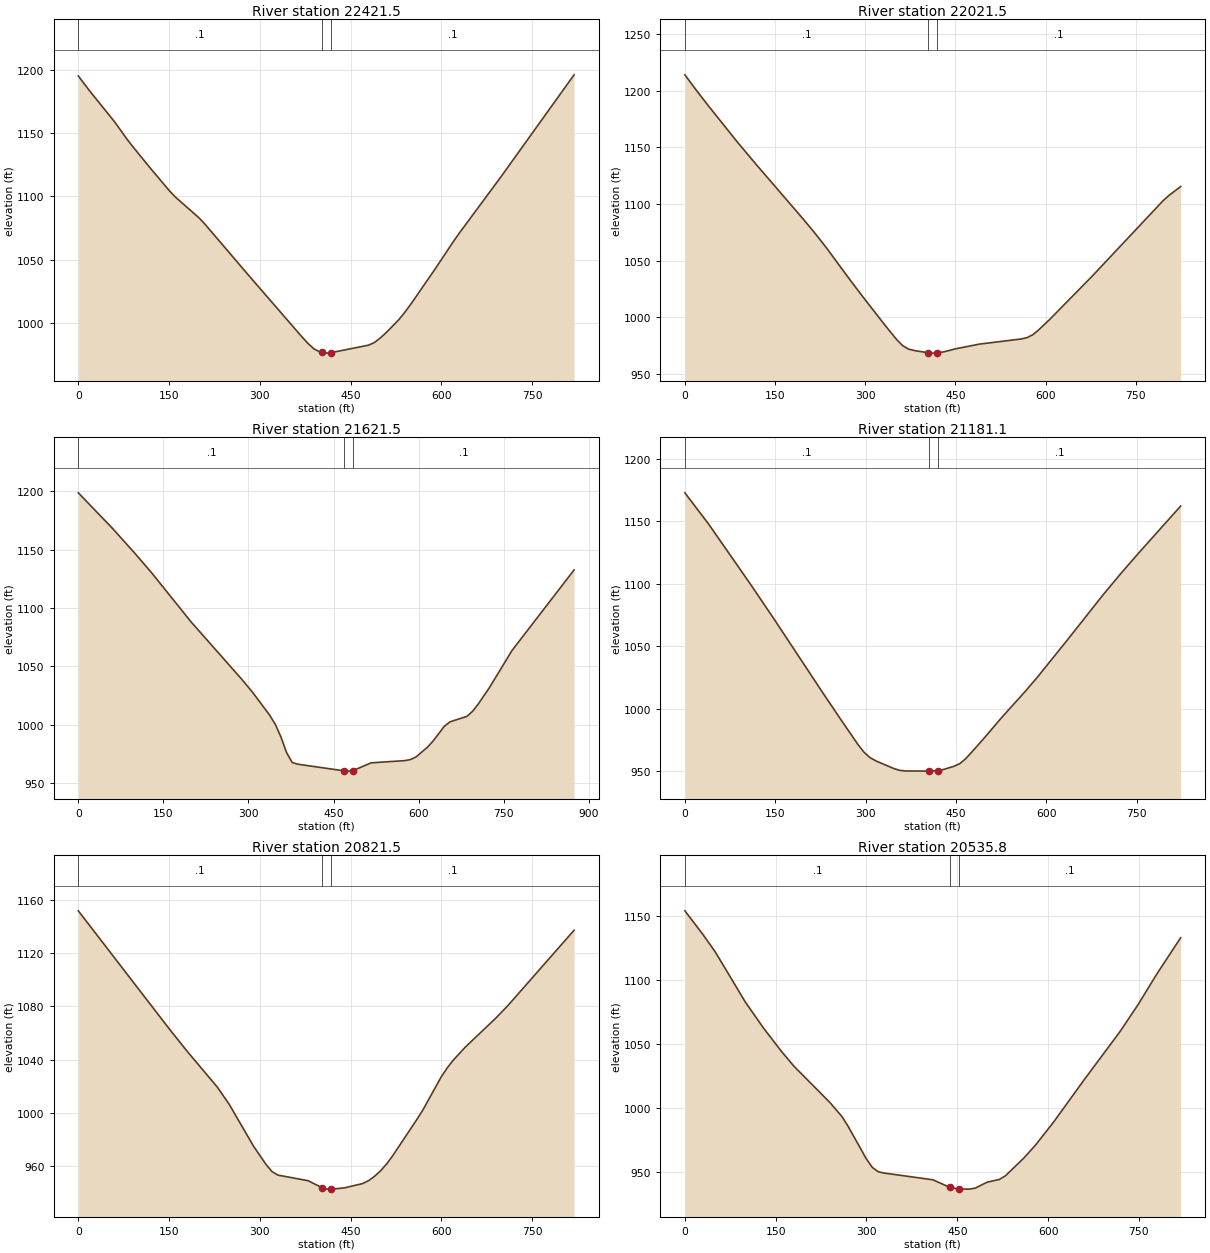
Type RM Length L Ch R = 1 ,22421.5 ,400.6,399.9,397.5
XS GIS Cut Line= 3
     1896697.758      440279.886     1896487.792      440631.454
     1896273.262      440980.371
#Sta/Elev= 30
       0 1195.39      20 1182.78    59.9 1159.09    79.9 1145.68    89.9 1139.49
   119.8 1121.92   149.8 1104.87   159.8 1099.74   199.8 1082.88   209.7 1077.77
   279.6 1038.52   369.5  988.77   379.5  983.57   389.5  979.22   399.5  976.76
     402  976.55   409.5  975.91     417  976.22   479.4   982.2   489.4  984.38
   499.4  988.11   509.4  992.49   529.4 1002.33   539.4 1008.23   549.4 1014.69
   589.3 1042.37   619.3 1064.01   629.3  1070.8   699.2 1116.12   819.1 1196.28
#Mann= 3 , 0 , 0
       0      .1       0     402    .045       0     417      .1       0
Bank Sta=402,417
XS Rating Curve= 0 ,0
Exp/Cntr=0.3,0.1

Type RM Length L Ch R = 1 ,22021.5 ,386,399.9,416.8
XS GIS Cut Line= 3
     1896369.804      440027.928     1896172.735      440388.897
     1895995.984      440762.356
#Sta/Elev= 30
       0 1213.94    19.6 1199.97    39.2 1186.55    88.1 1154.15   117.5 1135.57
   195.8 1087.37   215.4 1074.87     235 1061.68   274.2 1033.42   293.8 1019.71
   332.9  993.08   352.5  980.25   362.3  975.07   372.1  972.04   381.9  970.79
   403.8   968.9   411.3  968.52   418.8  968.64   430.9  969.67   450.6  972.38
     490  976.49   558.8  980.97   568.7  982.11   578.5  984.69   588.3  988.98
     608  998.93   676.9 1036.16   794.9 1102.77   804.8  1107.5   824.4 1115.41
#Mann= 3 , 0 , 0
       0      .1       0   403.8    .045       0   418.8      .1       0
Bank Sta=403.8,418.8
XS Rating Curve= 0 ,0
Exp/Cntr=0.3,0.1

Type RM Length L Ch R = 1 ,21621.5 ,424.2,440.4,455
XS GIS Cut Line= 3
     1896285.654      439954.027     1895856.317      440160.445
     1895486.704      440307.242
#Sta/Elev= 30
       0 1198.56    59.6 1168.49    99.2 1147.07     129 1130.28   198.5 1088.25
   287.8 1039.18   307.7 1027.53   337.4 1008.23   347.4 1000.33   357.3  989.52
   367.2  976.24   377.1  967.73   387.1  966.27   468.9  960.56   476.4  960.34
   483.9  960.71   516.2  967.43   575.8  969.34   585.8  970.26   595.7  972.57
   615.6  980.84   625.5  986.09   645.4  998.77   655.3 1002.53   685.2 1007.23
   695.1 1011.52   705.1 1017.73   724.9 1031.85   764.7 1063.62   874.1 1132.55
#Mann= 3 , 0 , 0
       0      .1       0   468.9    .045       0   483.9      .1       0
Bank Sta=468.9,483.9
XS Rating Curve= 0 ,0
Exp/Cntr=0.3,0.1

Type RM Length L Ch R = 1 ,21181.1 ,358.6,359.6,360.8
XS GIS Cut Line= 2
     1896279.834      439842.863     1895485.923      439626.258
#Sta/Elev= 30
       0 1172.85    39.7 1147.63   109.1  1099.5   148.7 1071.25     228 1013.36
   257.8  991.99   287.5  971.12   297.4  965.04   307.4  960.71   317.3  958.04
     347  951.96   356.9   950.5   366.8  950.04   405.6  949.94   406.5  949.92
   420.6  950.35   426.3  950.82   446.2  953.71   456.1  955.83     466  959.81
   475.9  965.01   495.7  975.77   525.5  992.66   565.1 1013.88     585 1025.08
   634.6  1054.8     694 1091.03   723.8  1108.3   753.5 1124.77   822.9 1162.22
#Mann= 3 , 0 , 0
       0      .1       0   405.6    .045       0   420.6      .1       0
Bank Sta=405.6,420.6
XS Rating Curve= 0 ,0
Exp/Cntr=0.3,0.1

Type RM Length L Ch R = 1 ,20821.5 ,280.9,285.8,290.3
XS GIS Cut Line= 3
      1896368.45      439512.307     1895977.886      439388.962
     1895589.482       439259.21
#Sta/Elev= 30
       0 1151.97   149.8  1063.4   179.8 1046.28   229.8 1019.23   249.7 1006.04
   289.7   974.7   309.7  961.38   319.7  955.85   329.7  953.08   379.6  948.87
   402.1  943.74   409.6  942.59   417.1  942.54   419.6  942.52   439.5  943.45
   469.5  946.68   479.5  948.87   489.5  952.19   499.5  956.39   509.5   961.5
   519.4  967.61   559.4  994.98   569.4 1002.16   599.4 1026.85   609.3 1033.63
   619.3 1039.46   639.3 1049.38   689.2 1070.96   709.2 1080.37   819.1 1137.36
#Mann= 3 , 0 , 0
       0      .1       0   402.1    .045       0   417.1      .1       0
Bank Sta=402.1,417.1
XS Rating Curve= 0 ,0
Exp/Cntr=0.3,0.1

Type RM Length L Ch R = 1 ,20535.8 ,225.8,223.4,221
XS GIS Cut Line= 3
     1896448.388        439345.4     1896096.703      439135.514
     1895742.008      438930.883
#Sta/Elev= 30
       0 1154.17      30 1135.58      50 1122.24    99.9  1082.9   129.9  1062.6
   159.8 1044.24   179.8    1033   239.7  1004.4   259.7  993.36   269.7  985.84
   299.7  960.48   309.7  953.72   319.6  950.34   329.6  949.29   409.6  944.09
   437.4  938.21   452.4  936.89   469.5  936.78   479.5  937.51   499.4  942.22
   519.4  944.32   529.4  947.14   559.4  960.75   579.3  971.21   609.3  989.25
   659.2 1021.92   719.2 1060.05   749.1 1081.21   779.1 1104.37     819 1133.13
#Mann= 3 , 0 , 0
       0      .1       0   437.4    .045       0   452.4      .1       0
Bank Sta=437.4,452.4
XS Rating Curve= 0 ,0
Exp/Cntr=0.3,0.1

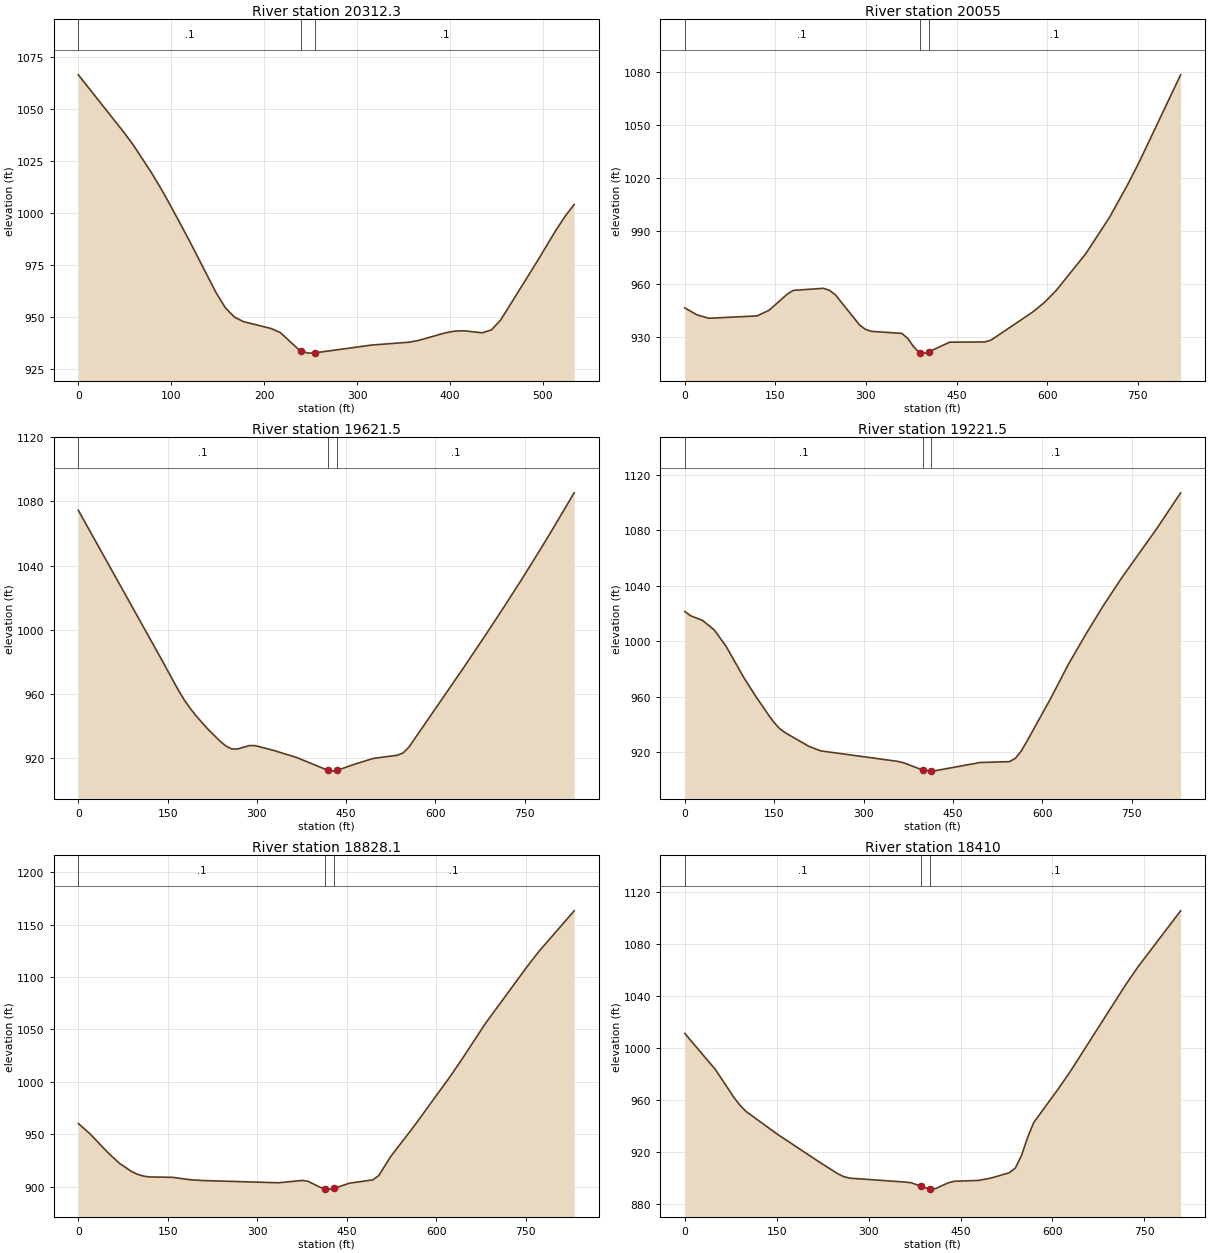
Type RM Length L Ch R = 1 ,20312.3 ,269.8,257.3,245.6
XS GIS Cut Line= 2
     1896404.153      439024.912     1895915.999      438809.029
#Sta/Elev= 30
       0  1066.3    49.4  1038.5    59.3 1032.54    79.1 1019.04      89 1011.68
    98.8 1003.89   118.6  987.49   148.3  961.72   158.2  954.52     168  950.01
   177.9   947.8   207.6  944.51   217.5  942.56   237.2  934.46   240.1  933.94
   247.1   932.7   255.1  932.86   316.3   936.6   355.8  937.93   365.7  938.73
   395.4  942.46   405.3  943.26   415.2  943.42   434.9  942.46   444.8  943.87
   454.7  948.62   494.2   976.9     514  991.56   523.9  998.29   533.8 1004.07
#Mann= 3 , 0 , 0
       0      .1       0   240.1    .045       0   255.1      .1       0
Bank Sta=240.1,255.1
XS Rating Curve= 0 ,0
Exp/Cntr=0.3,0.1

Type RM Length L Ch R = 1 ,20055   ,433.4,433.5,434.2
XS GIS Cut Line= 3
     1896620.898      438631.644     1896215.405       438685.71
     1895804.235      438709.715
#Sta/Elev= 30
       0  946.57      20  942.65    39.9  940.71   119.7  942.04   139.7  945.24
   169.6   954.3   179.6  956.45   229.5  957.63   239.5  956.48   249.4  953.96
   289.4  936.92   299.3   934.4   309.3   933.3   359.2  932.18   369.2  929.34
   379.2  924.48   388.8  921.25   399.1  921.02   403.8  921.72   438.5   927.2
   497.3  927.34   507.2   928.4   575.8  944.16   595.4  949.62     615  956.43
     664  977.19   703.3  997.74   732.7  1015.8   752.3 1028.85     821 1078.19
#Mann= 3 , 0 , 0
       0      .1       0   388.8    .045       0   403.8      .1       0
Bank Sta=388.8,403.8
XS Rating Curve= 0 ,0
Exp/Cntr=0.3,0.1

Type RM Length L Ch R = 1 ,19621.5 ,412.4,400,385.4
XS GIS Cut Line= 3
     1896547.923      438212.996     1896124.467      438266.609
     1895718.927      438293.642
#Sta/Elev= 30
       0  1074.5     139  982.13   168.8  961.97   178.7  955.97   188.6  950.79
   198.5  946.16   218.4  937.89   238.2  930.65   248.2  927.57   258.1  925.77
     268  925.82   287.9  927.94   297.8  927.82   327.6  924.96   367.3  920.42
   419.3  912.51   426.8  911.98   434.3  912.38   466.5  916.56   496.2  919.92
   535.9  921.86   545.8  923.31   555.7  926.98   644.9  975.02   684.6   996.9
   714.3 1013.68   744.1 1030.84   773.8 1048.52   793.6 1060.55   833.3 1085.37
#Mann= 3 , 0 , 0
       0      .1       0   419.3    .045       0   434.3      .1       0
Bank Sta=419.3,434.3
XS Rating Curve= 0 ,0
Exp/Cntr=0.3,0.1

Type RM Length L Ch R = 1 ,19221.5 ,402.5,392.9,384.2
XS GIS Cut Line= 3
     1896323.753      437664.477     1896002.765      437914.133
     1895676.972      438188.094
#Sta/Elev= 30
       0  1021.3     9.9 1018.21    29.8  1014.9    49.6    1008    69.4  996.15
    99.2  973.64     119  960.27   138.8  947.87   148.8  941.92   158.7  937.18
   168.6     934   208.3  924.18   228.1  920.92   357.1  913.38     367  912.38
   399.1  907.15   414.1  906.35   416.6  906.33   495.7  912.54   545.2  913.17
   555.1  915.63     565  920.99   574.9  928.27   614.5  958.95   644.2   983.5
   673.9 1005.46   703.6 1026.23   733.3  1045.5   792.7 1081.29   832.3  1106.8
#Mann= 3 , 0 , 0
       0      .1       0   399.1    .045       0   414.1      .1       0
Bank Sta=399.1,414.1
XS Rating Curve= 0 ,0
Exp/Cntr=0.3,0.1

Type RM Length L Ch R = 1 ,18828.1 ,416.6,417.8,418.9
XS GIS Cut Line= 3
     1895874.976      437352.933     1895674.002      437727.014
     1895479.191      438084.165
#Sta/Elev= 30
       0  960.36    19.8  950.41    49.4  932.67    69.1  922.37    88.9  914.69
    98.8  912.02   108.6  910.29   118.5  909.42     158  909.04   187.6  906.73
   207.4  906.01   335.8  903.85   375.3  906.05   385.2  905.26   404.9  899.74
   413.7  898.01   414.8  897.79   424.6  897.81   428.7  898.47   454.4  903.41
   494.1  906.67     504  910.83   523.9  928.92   563.6  958.24   623.1 1004.79
     643 1021.33   682.6 1055.63   752.1 1109.48   771.9 1124.02   831.5 1163.06
#Mann= 3 , 0 , 0
       0      .1       0   413.7    .045       0   428.7      .1       0
Bank Sta=413.7,428.7
XS Rating Curve= 0 ,0
Exp/Cntr=0.3,0.1

Type RM Length L Ch R = 1 ,18410   ,359.4,346.4,333.5
XS GIS Cut Line= 2
     1895571.013      437111.704      1895150.54      437802.921
#Sta/Elev= 30
       0  1011.2    49.9  983.44    79.9  962.17    89.9  956.02    99.9   951.2
   149.8  934.07   219.7  912.18   249.7  903.22   259.7  900.92   269.7   899.8
   359.6  896.82   369.6  896.27   385.2  893.66   399.5  891.38   400.2  891.41
   409.5  891.82   429.5  896.18   439.5  897.42   479.4   898.1   499.4  899.86
   529.4  903.94   539.4  907.59   549.4  917.25   559.4  931.08   569.3  942.55
   609.3  968.43   629.3   982.1   719.2 1048.48   739.1 1062.17   809.1 1105.56
#Mann= 3 , 0 , 0
       0      .1       0   385.2    .045       0   400.2      .1       0
Bank Sta=385.2,400.2
XS Rating Curve= 0 ,0
Exp/Cntr=0.3,0.1

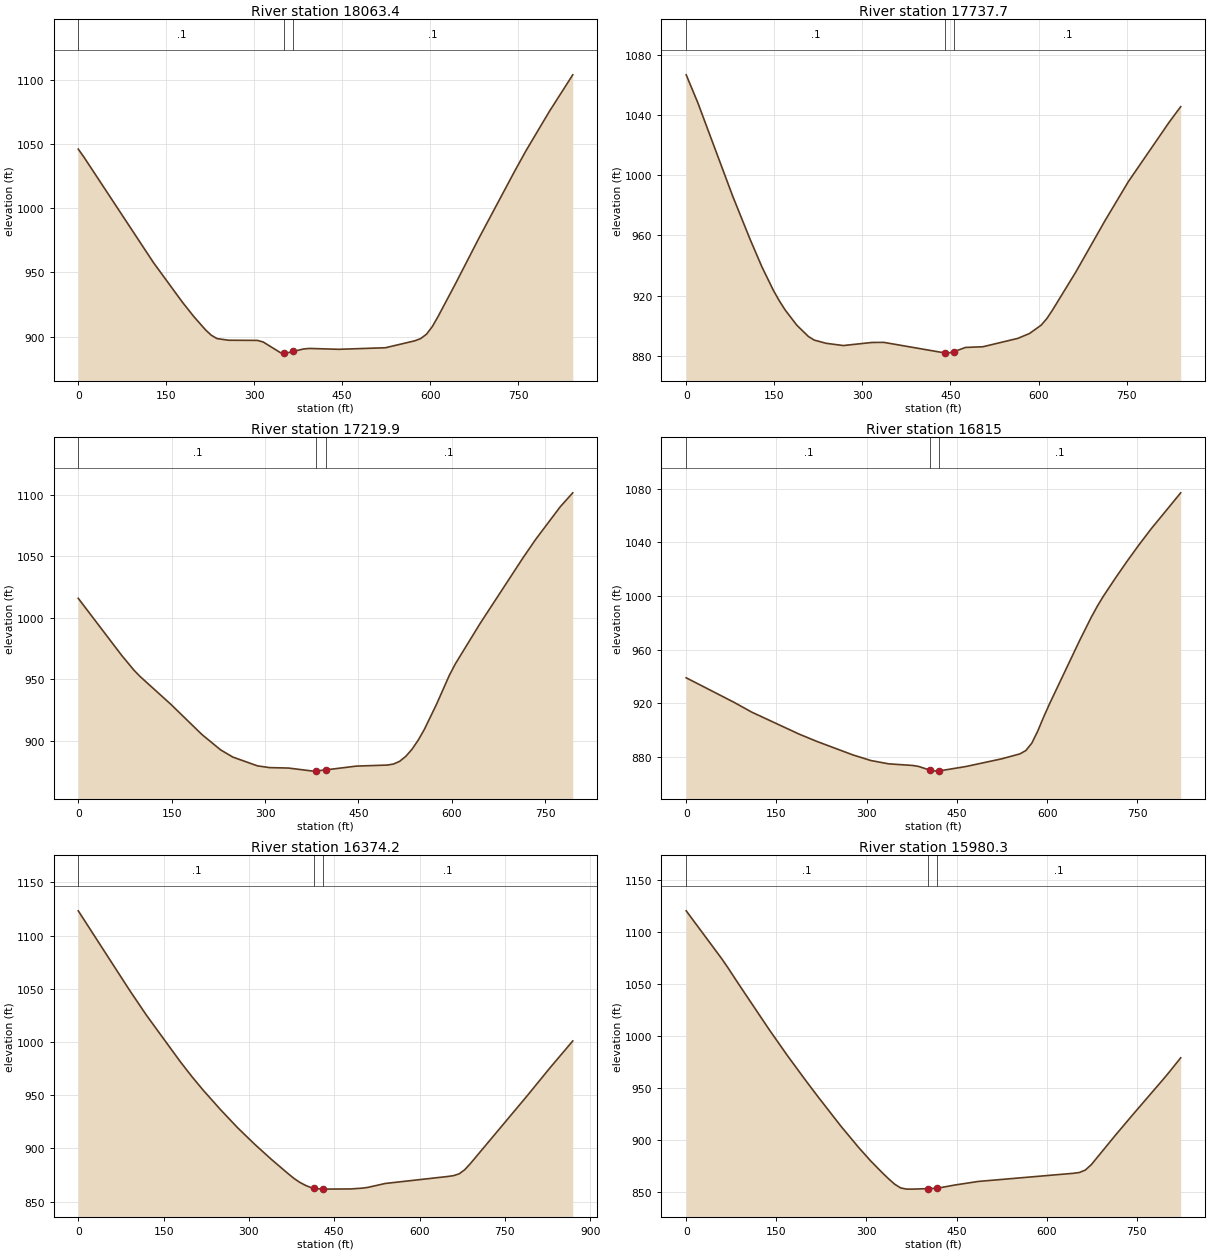
Type RM Length L Ch R = 1 ,18063.4 ,323.3,325.5,327.7
XS GIS Cut Line= 3
     1895040.876      436956.486     1895052.089       437360.43
     1895057.415      437799.467
#Sta/Elev= 30
       0 1045.94     9.9 1039.56   128.1  957.72   177.4  926.93   197.1   915.6
   216.8  905.38   226.7  901.14   236.6  898.48   256.3   897.2   305.5  897.08
   315.4  895.82     345  887.47   351.5  887.27   354.8  887.17   366.5  888.47
   384.4  890.42   394.2  890.82     444  890.14   523.8  891.36   573.7  896.74
   583.7  898.45   593.7  901.84   603.7  907.83   613.7   915.8   643.6  941.52
   683.5  976.91   743.4 1028.13   763.3 1044.57   803.2 1075.18   843.2 1103.76
#Mann= 3 , 0 , 0
       0      .1       0   351.5    .045       0   366.5      .1       0
Bank Sta=351.5,366.5
XS Rating Curve= 0 ,0
Exp/Cntr=0.3,0.1

Type RM Length L Ch R = 1 ,17737.7 ,525.8,517.8,512.9
XS GIS Cut Line= 2
     1894776.806      436924.609     1894709.556       437763.95
#Sta/Elev= 30
       0  1066.7    19.8 1048.15    79.2  986.11     109  957.28   128.8  939.28
   148.6  923.46   158.5  916.65   168.4   910.6   188.2   900.5     208  892.96
   217.9  890.56   237.8  888.44   267.5  886.91     317  888.99   336.8     889
   441.4  881.94   445.8  881.88   456.4   882.9   475.5  885.65   505.2  886.11
   564.7  891.68   584.5   894.9   604.3  900.41   614.2  904.89   624.1  910.72
   663.7  935.93   713.2   969.9   752.9  995.79   822.2 1035.14     842 1045.55
#Mann= 3 , 0 , 0
       0      .1       0   441.4    .045       0   456.4      .1       0
Bank Sta=441.4,456.4
XS Rating Curve= 0 ,0
Exp/Cntr=0.3,0.1

Type RM Length L Ch R = 1 ,17219.9 ,398.5,403.8,406
XS GIS Cut Line= 2
     1894340.361       436972.23     1894369.076      437766.001
#Sta/Elev= 30
       0 1015.84    69.5  969.54    89.4  957.35    99.3  952.18   148.9  929.43
   198.6  904.94   228.4   892.5   248.2  886.56   287.9  879.37   307.8  877.94
   337.6   877.6   377.3  875.09   382.3  875.27   397.3  876.09   446.8  879.18
   496.4  880.03   506.4  880.86   516.3   883.1   526.2  887.15   536.2  892.97
   546.1  900.34     556  909.14   575.9  930.02   595.7  952.73   605.6  962.37
   645.4  995.29   714.9 1049.22   734.7 1063.82   774.4 1090.54   794.3 1101.77
#Mann= 3 , 0 , 0
       0      .1       0   382.3    .045       0   397.3      .1       0
Bank Sta=382.3,397.3
XS Rating Curve= 0 ,0
Exp/Cntr=0.3,0.1

Type RM Length L Ch R = 1 ,16815   ,450.5,440.7,431
XS GIS Cut Line= 2
     1894011.634      436955.882     1894037.672      437777.404
#Sta/Elev= 30
       0  938.92    79.2   920.7   108.9  913.33   188.2  896.83   217.9  891.36
   277.3  881.38     307  877.23   336.7  874.75   376.3  873.56   386.2  872.84
   405.9  869.95   415.9  869.33   420.9   869.5   465.4  872.81   524.8  878.54
   554.6  882.18   564.5  884.67   574.4  890.16   584.3   899.2   594.2  909.77
   604.1  919.69   653.6  966.42   673.4  984.18   683.3  992.27   693.2  999.62
     713 1012.99   732.8 1025.82   752.6 1038.08   772.4 1049.75   821.9 1076.83
#Mann= 3 , 0 , 0
       0      .1       0   405.9    .045       0   420.9      .1       0
Bank Sta=405.9,420.9
XS Rating Curve= 0 ,0
Exp/Cntr=0.3,0.1

Type RM Length L Ch R = 1 ,16374.2 ,402.6,393.7,384.6
XS GIS Cut Line= 2
     1893400.963      437023.507     1893791.879       437800.09
#Sta/Elev= 30
       0 1123.19    89.9 1048.86   119.9 1025.13   179.9  981.12   199.9  967.42
   219.8   954.6   249.8   936.6   279.8  919.62   309.8   904.1   339.8  889.59
   369.8  875.92   379.8  871.62   389.7  868.05   399.7  865.25   409.7  863.11
   415.1  862.47   429.7  861.76   430.1  861.77   479.7  861.95   499.7  862.69
   509.7  863.45   539.6  867.06   649.6  873.64   659.6   874.4   669.6   876.1
   679.6  880.04   689.5   885.8   789.5  949.59   829.4  975.72   869.4 1000.93
#Mann= 3 , 0 , 0
       0      .1       0   415.1    .045       0   430.1      .1       0
Bank Sta=415.1,430.1
XS Rating Curve= 0 ,0
Exp/Cntr=0.3,0.1

Type RM Length L Ch R = 1 ,15980.3 ,366.1,358.8,352.8
XS GIS Cut Line= 2
     1892980.671      437370.301     1893599.793      437912.712
#Sta/Elev= 30
       0 1120.21    59.5 1073.94    69.4 1065.61    89.2 1048.22   138.8 1005.57
   168.6  981.07   198.3  957.73   218.2  942.52   257.8  913.15   287.6  892.51
   307.4  879.76   327.3  868.08   337.2  862.62   347.1  857.56     357     854
   366.9  852.88   376.8  852.86   402.3  853.35   417.3  853.64   446.3  856.73
   485.9  860.22   644.6  868.07   654.5  868.84   664.4  871.19   674.4  876.42
     714  904.34   743.8  924.68   793.4  957.93   803.3  964.76   823.1     979
#Mann= 3 , 0 , 0
       0      .1       0   402.3    .045       0   417.3      .1       0
Bank Sta=402.3,417.3
XS Rating Curve= 0 ,0
Exp/Cntr=0.3,0.1

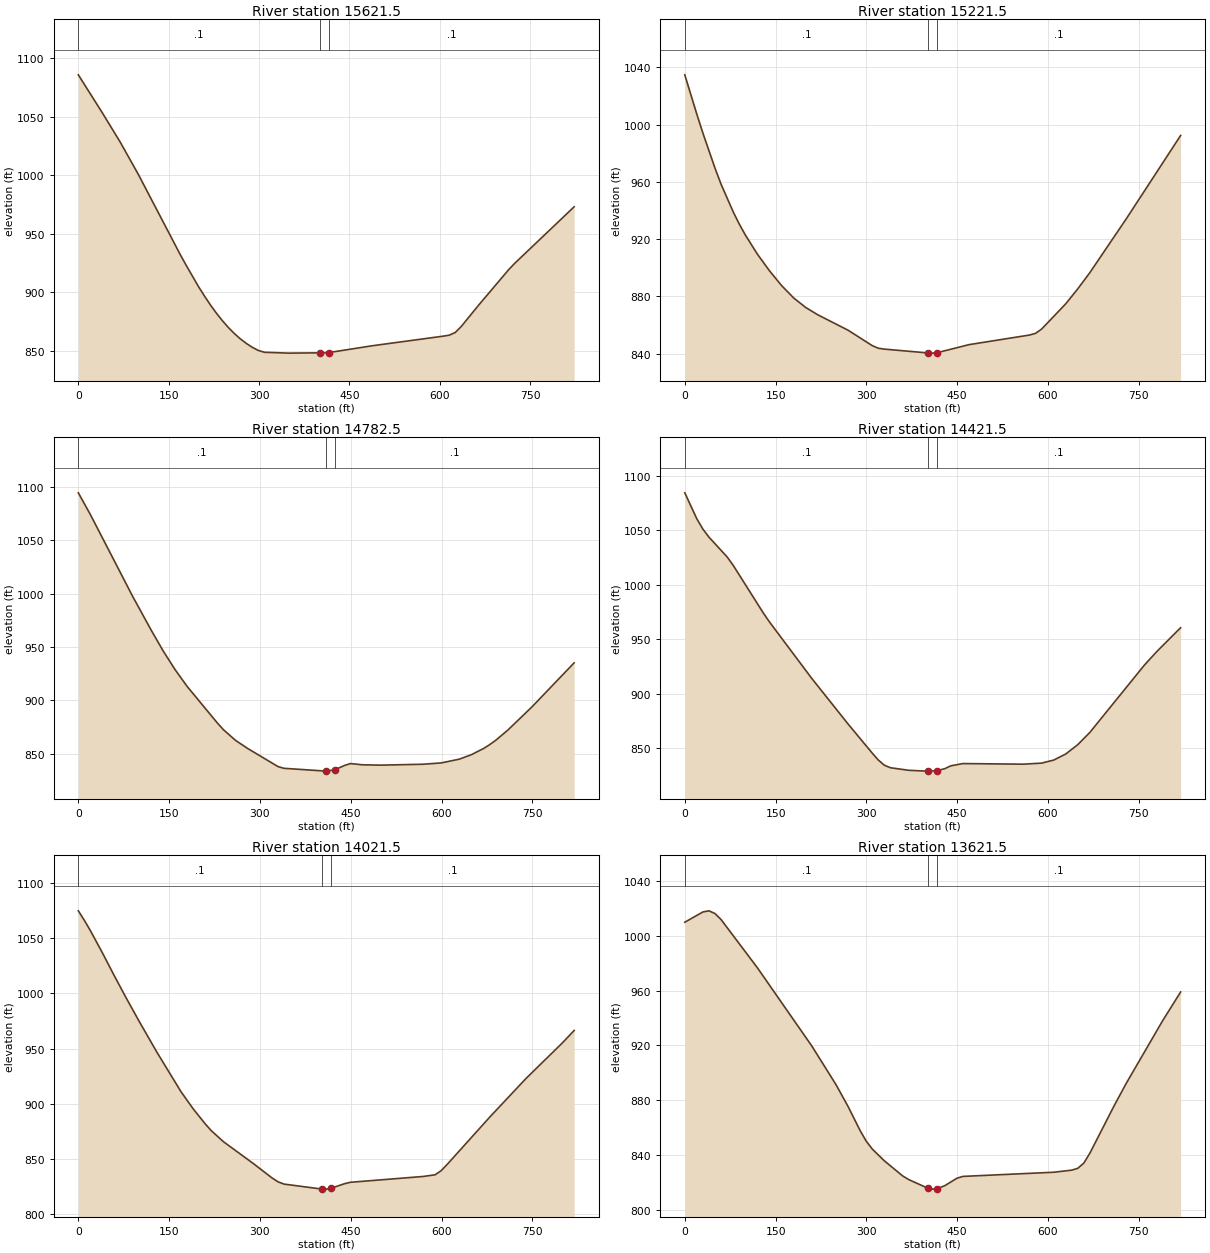
Type RM Length L Ch R = 1 ,15621.5 ,389.5,400,409.1
XS GIS Cut Line= 3
     1892699.756      437771.375      1893076.97      437928.549
     1893448.999      438110.912
#Sta/Elev= 30
       0 1085.87    39.9 1053.32    69.8 1028.08    99.7 1000.59   169.4  931.85
   179.4  922.57   199.3  904.84   209.3  896.68   219.3  888.98   229.2  881.95
   239.2  875.48   249.2  869.63   259.1  864.47   269.1   859.9   279.1     856
     289  852.67     299  850.01     309   848.5   348.8  847.77   401.1  848.02
   416.1  848.27   487.6  854.05   605.9   862.3   615.8  863.15   625.7  865.46
   635.5   870.5   665.1  889.22   714.5  919.29   724.3  924.58     823  972.97
#Mann= 3 , 0 , 0
       0      .1       0   401.1    .045       0   416.1      .1       0
Bank Sta=401.1,416.1
XS Rating Curve= 0 ,0
Exp/Cntr=0.3,0.1

Type RM Length L Ch R = 1 ,15221.5 ,435.3,439.1,443
XS GIS Cut Line= 3
     1892571.847      437931.079     1892839.723      438240.809
     1893107.598       438550.54
#Sta/Elev= 30
       0 1034.81      20 1007.14      30  993.97    49.9  969.58    59.9  958.39
    79.9  939.11    89.9  930.61    99.9  922.98   119.8   909.6   139.8  897.93
   159.8   887.6   179.8  878.92   199.8  872.23   219.7  867.13   269.7  856.37
   309.6   845.6   319.6  843.78   329.6  843.15     402  840.47   409.5  840.35
     417  840.67   469.4  846.27   569.3  852.98   579.3  854.15   589.3  857.12
   629.2  874.78   649.2  885.31   669.2  896.67   729.1  934.12     819  992.43
#Mann= 3 , 0 , 0
       0      .1       0     402    .045       0     417      .1       0
Bank Sta=402,417
XS Rating Curve= 0 ,0
Exp/Cntr=0.3,0.1

Type RM Length L Ch R = 1 ,14782.5 ,362.3,360.9,359.4
XS GIS Cut Line= 3
      1892277.94      438158.667     1892492.833      438507.314
     1892702.606      438858.993
#Sta/Elev= 30
       0 1094.62      20 1074.14    89.9  997.38   119.9  966.36   139.8   946.7
   159.8  928.88   179.8  913.08   229.8  878.75   239.7  872.55   259.7  862.54
   279.7  854.98   329.6  838.04   339.6  836.36   408.6  833.75   409.6  833.72
   423.6  834.96   439.5     839   449.5  840.79   469.5  839.65   499.4  839.32
   569.4  840.18   599.3   841.4   629.3  844.93   649.2  849.12   669.2  854.87
   679.2  858.45   689.2  862.52   709.2  872.05   749.1  893.84     819  935.26
#Mann= 3 , 0 , 0
       0      .1       0   408.6    .045       0   423.6      .1       0
Bank Sta=408.6,423.6
XS Rating Curve= 0 ,0
Exp/Cntr=0.3,0.1

Type RM Length L Ch R = 1 ,14421.5 ,396,400,404.4
XS GIS Cut Line= 3
     1891954.754      438365.595     1892188.701      438701.689
     1892422.648      439037.782
#Sta/Elev= 30
       0 1084.61      20 1060.57      30 1051.15      40  1043.8    69.9 1025.67
    79.9 1017.96   129.8  973.99   139.8   965.9   209.7  913.93   269.7  871.96
   309.6  845.21   319.6  838.86   329.6  834.06   339.6  831.75   369.6  829.39
   399.5  828.62     402  828.63     417  829.08   429.5  830.89   439.5  833.51
   459.4  835.57   559.3  835.01   589.3  835.98   609.3  838.77   629.2  844.36
   649.2  852.99   669.2  864.32   759.1  926.11     779  938.22     819  960.56
#Mann= 3 , 0 , 0
       0      .1       0     402    .045       0     417      .1       0
Bank Sta=402,417
XS Rating Curve= 0 ,0
Exp/Cntr=0.3,0.1

Type RM Length L Ch R = 1 ,14021.5 ,390.8,400,408.7
XS GIS Cut Line= 3
     1891677.333      438539.344     1891848.675      438911.389
     1892012.299      439286.759
#Sta/Elev= 30
       0 1074.75      10 1066.08      20 1056.75      40 1036.48    59.9 1015.47
    79.9  995.04    99.9  975.26   129.9  946.64   169.8   910.8   189.8  895.38
   209.8  881.69   219.8  875.59   239.8  865.66   289.7  845.67   319.7  832.98
   329.7  829.41   339.7   827.3   402.1   822.8   409.6  822.73   417.1  823.44
   439.6  827.62   449.6  828.93   569.4  834.18   589.4   835.7   599.4  839.43
   609.4  845.14   679.3  887.73   739.2  922.73   799.1  954.86   819.1  966.38
#Mann= 3 , 0 , 0
       0      .1       0   402.1    .045       0   417.1      .1       0
Bank Sta=402.1,417.1
XS Rating Curve= 0 ,0
Exp/Cntr=0.3,0.1

Type RM Length L Ch R = 1 ,13621.5 ,341,348,355.1
XS GIS Cut Line= 3
     1891455.156      438583.131     1891465.789      438992.493
     1891476.421      439401.855
#Sta/Elev= 30
       0 1009.94      30 1017.45      40 1018.26    49.9 1016.27    59.9 1011.89
   119.8  976.73   209.7  919.59   249.7  891.36   269.7  875.35   289.6  857.76
   299.6   850.1   309.6   844.3   329.6  835.67   359.6  824.71   369.6     822
     402  815.57   409.5  814.98     417  815.38   429.5   817.5   449.4  822.92
   459.4  824.27   609.3  827.31   639.2  828.84   649.2  830.21   659.2  834.03
   669.2  841.33   709.1  875.82   729.1  892.19     789  937.78     819  958.96
#Mann= 3 , 0 , 0
       0      .1       0     402    .045       0     417      .1       0
Bank Sta=402,417
XS Rating Curve= 0 ,0
Exp/Cntr=0.3,0.1