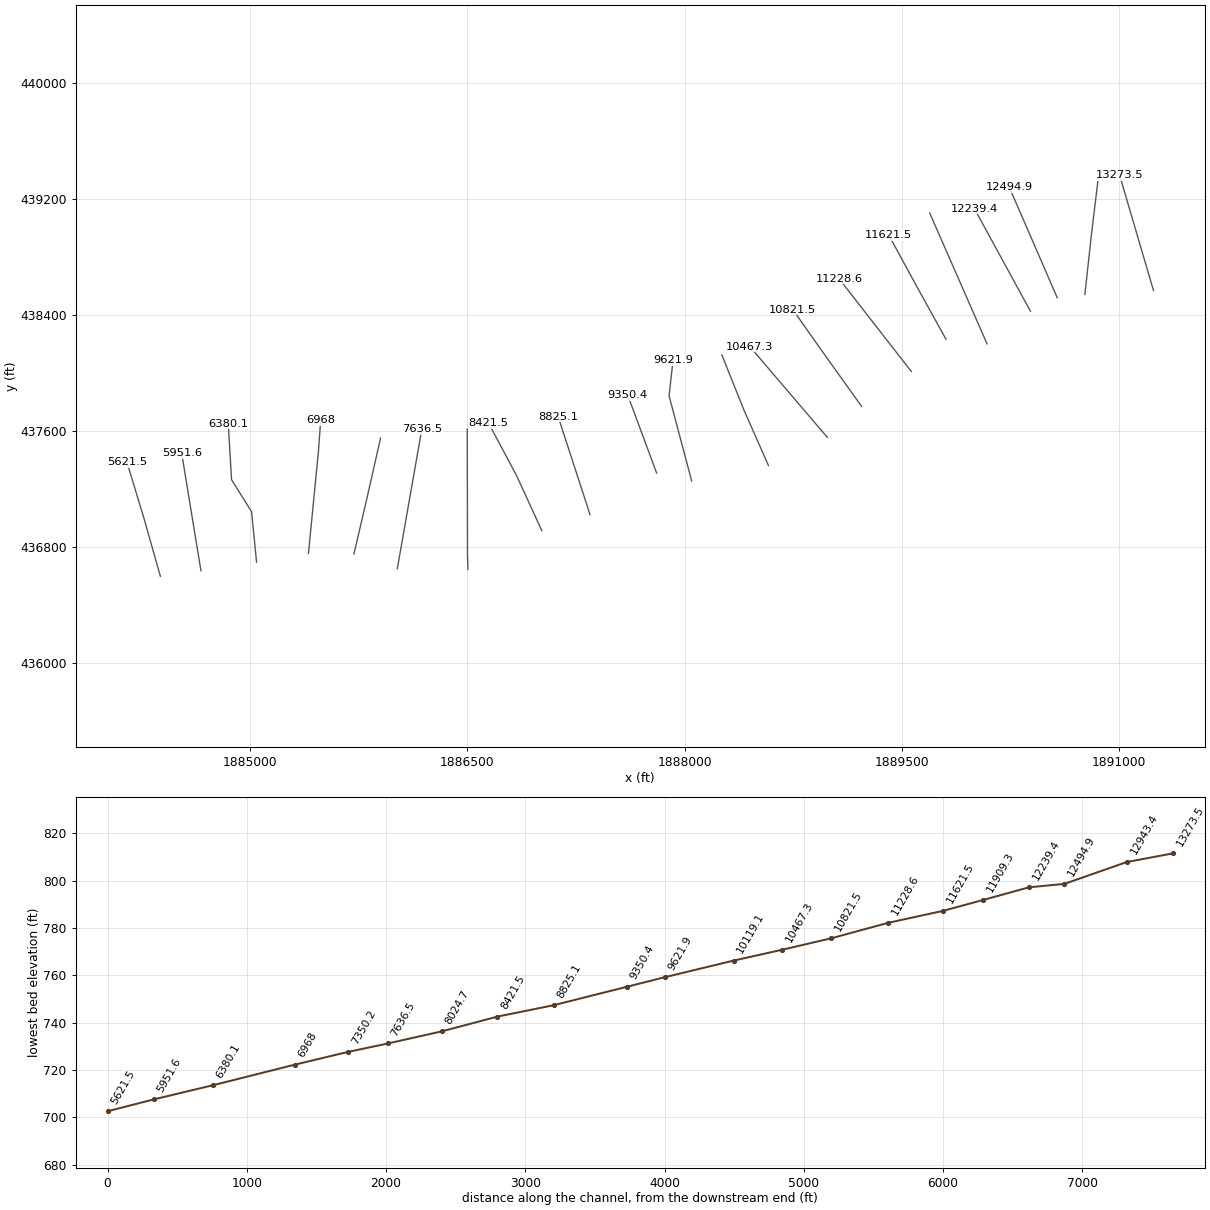
HEC-RAS study SmithersCk.prj: SmithersCk

--- SmithersCk.g01 (geometry) --- (continued)

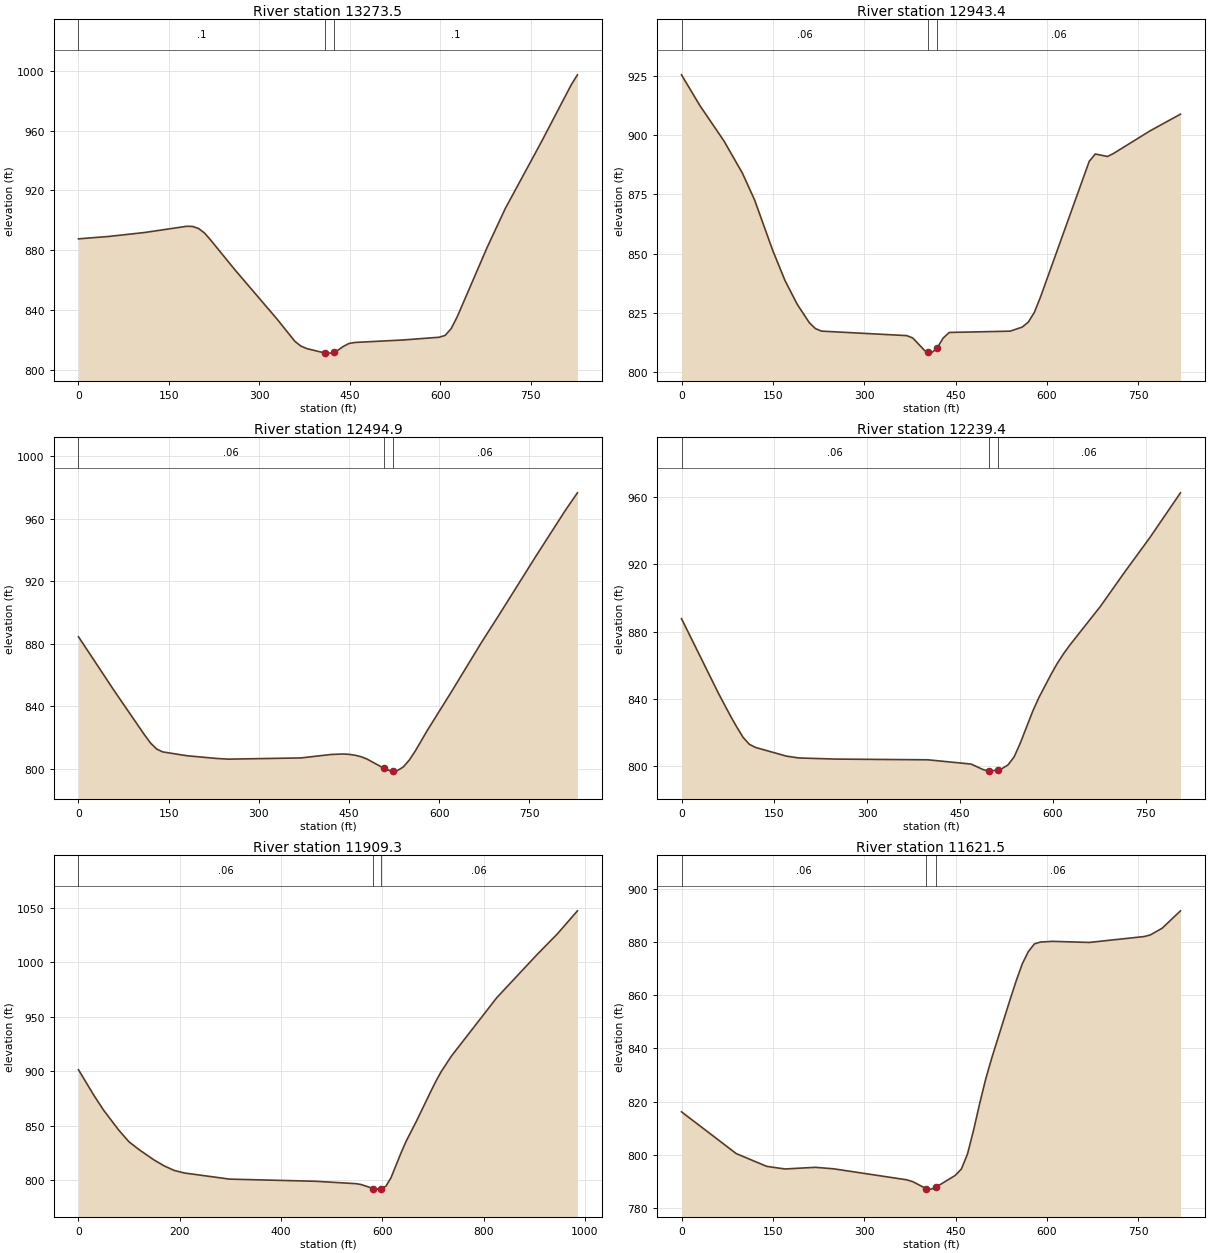
Type RM Length L Ch R = 1 ,13273.5 ,339.3,330.1,320.7
XS GIS Cut Line= 2
     1891237.996      438570.885      1891004.82      439364.824
#Sta/Elev= 30
       0  887.74    49.8  889.32   109.7  891.97   179.4  896.12   189.4  896.01
   199.4  894.59   209.4  891.48   219.3   886.9   259.2  867.21     329  834.36
   358.9  819.37   368.9  816.19   378.8   814.5   408.5   811.6   418.7   811.5
   423.5  812.21   428.7  812.98   438.7  815.86   448.6  817.94   458.6  818.63
   538.4  820.27   598.2   822.1   608.1  823.32   618.1  827.86   628.1  835.73
   677.9  882.16   707.8  907.94   767.7  952.41   817.5  990.72   827.5  997.16
#Mann= 3 , 0 , 0
       0      .1       0   408.5    .045       0   423.5      .1       0
Bank Sta=408.5,423.5
XS Rating Curve= 0 ,0
Exp/Cntr=0.3,0.1

Type RM Length L Ch R = 1 ,12943.4 ,436.6,448.3,460.3
XS GIS Cut Line= 3
     1890764.401      438543.338     1890808.828       438950.45
     1890858.032      439356.978
#Sta/Elev= 30
       0  925.58      30  912.64    69.9  897.52    99.9  884.02   119.9   872.7
   149.8  851.26   169.8  838.62   189.8  828.56   209.8  820.74   219.8  818.25
   229.7  817.18   369.6  815.28   379.6  814.28   399.5  808.86   404.1   808.4
   409.5  807.87   419.1  809.84   429.5  814.24   439.5  816.61   539.4  817.16
   559.3  818.89   569.3     821   579.3  825.17   589.3  831.64   669.2  888.98
   679.2  892.09   699.2  891.04   709.2  892.33   769.1  901.88     819  908.94
#Mann= 3 , 0 , 0
       0     .06       0   404.1    .045       0   419.1     .06       0
Bank Sta=404.1,419.1
XS Rating Curve= 0 ,0
Exp/Cntr=0.3,0.1

Type RM Length L Ch R = 1 ,12494.9 ,253.5,255.5,257.6
XS GIS Cut Line= 2
     1890573.376      438520.578      1890243.05      439281.837
#Sta/Elev= 30
       0  884.52      60  849.68     110  821.71     120  816.51     130  812.76
     140  810.94     180  808.49     230  806.72     250   806.3   369.9  807.07
   419.9  809.27   439.9  809.59   449.9  809.35   459.9  808.81   469.9  807.86
   479.9  806.35   507.4  800.57   519.9  798.64   522.4   798.7   529.9  798.88
   539.9  801.22   549.9  805.57   559.9  811.33   579.9  824.52   619.9  849.13
   669.9   880.7   699.9  898.76   759.8  935.44   809.8  965.37   829.8  976.51
#Mann= 3 , 0 , 0
       0     .06       0   507.4    .045       0   522.4     .06       0
Bank Sta=507.4,522.4
XS Rating Curve= 0 ,0
Exp/Cntr=0.3,0.1

Type RM Length L Ch R = 1 ,12239.4 ,332,330,328.1
XS GIS Cut Line= 2
     1890388.422      438427.477     1890001.765      439134.736
#Sta/Elev= 30
       0  887.74    59.7  843.37    79.6  829.61    89.6  823.17    99.5  817.22
   109.5  813.14   119.4  811.25   169.2   806.1   189.1     805   248.8  804.32
     398  803.89   467.7  801.37   487.6  798.02   496.1   797.3   497.6  797.17
   511.1  797.87   517.5  798.61   527.4  800.86   537.4  805.69   547.3  813.85
   567.2  832.63   577.2  840.79   597.1  854.76     607  861.16     617  866.81
   626.9  871.85   676.7  895.04   716.5  915.73   756.3  935.75     806  962.48
#Mann= 3 , 0 , 0
       0     .06       0   496.1    .045       0   511.1     .06       0
Bank Sta=496.1,511.1
XS Rating Curve= 0 ,0
Exp/Cntr=0.3,0.1

Type RM Length L Ch R = 1 ,11909.3 ,285.7,287.8,289.7
XS GIS Cut Line= 2
     1890088.457      438202.883     1889692.597      439105.361
#Sta/Elev= 30
       0  901.42    29.9  878.29    49.8  864.16    79.6  845.96    99.5  835.37
   119.4  828.17   149.3  818.56   169.2  813.17   189.1  808.97     209  806.64
   298.6     801   467.8  799.03   547.5  796.86   557.4  796.14   582.4  792.36
   587.3  791.82   597.4  792.03   607.2   794.5   617.2  802.22   637.1  825.12
     647  835.63   666.9  853.64   696.8  882.38   706.8  891.65   716.7  899.87
   736.6  913.95   826.2  967.56   905.8 1007.15   945.7 1026.03   985.5 1047.28
#Mann= 3 , 0 , 0
       0     .06       0   582.4    .045       0   597.4     .06       0
Bank Sta=582.4,597.4
XS Rating Curve= 0 ,0
Exp/Cntr=0.3,0.1

Type RM Length L Ch R = 1 ,11621.5 ,389.5,392.9,396.5
XS GIS Cut Line= 3
     1889805.278      438234.179     1889606.663      438592.303
     1889410.574      438951.799
#Sta/Elev= 30
       0  816.22    89.9  800.54   139.8  795.76   169.8  794.78   219.7   795.4
   249.7  794.84   369.6  790.72   379.6  790.02     402  787.36   409.5  787.22
     417  787.86   449.5   792.4   459.4  794.78   469.4  800.37   479.4  809.33
   489.4  819.33   499.4   828.6   509.4  836.53   539.4  858.39   549.3  865.32
   559.3  871.71   569.3  876.34   579.3  879.23   589.3  879.92   609.3  880.18
   669.2  879.77   759.1  881.97   769.1  882.54     789  885.11     819  891.63
#Mann= 3 , 0 , 0
       0     .06       0     402    .045       0     417     .06       0
Bank Sta=402,417
XS Rating Curve= 0 ,0
Exp/Cntr=0.3,0.1

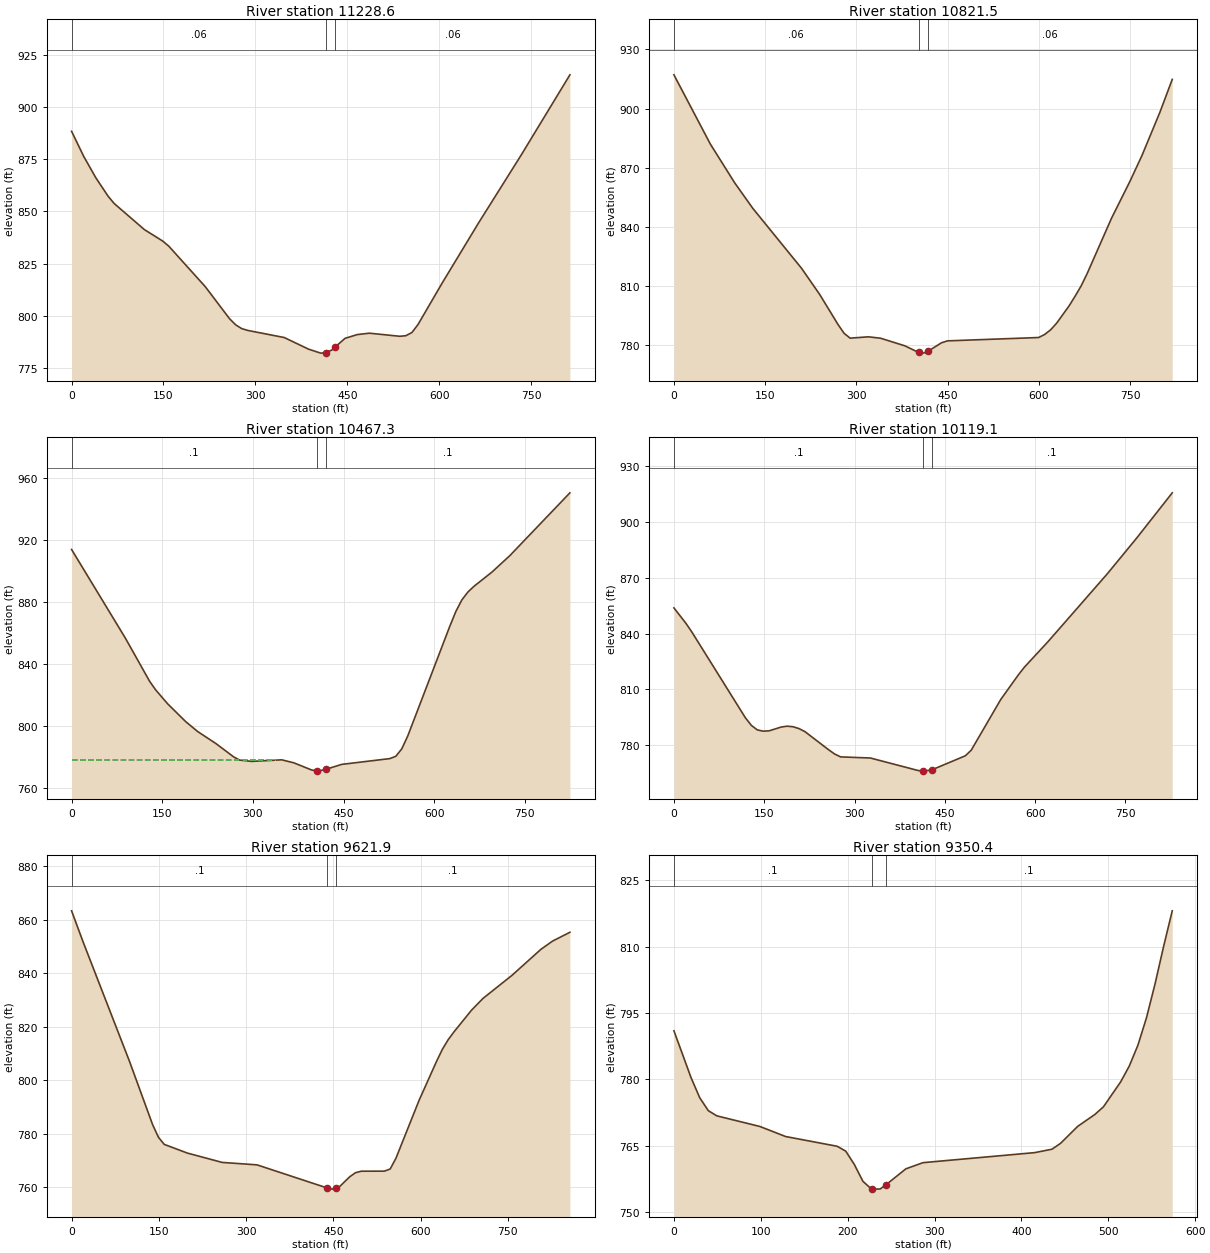
Type RM Length L Ch R = 1 ,11228.6 ,407.9,407.1,406.1
XS GIS Cut Line= 2
     1889566.199      438011.106     1889066.247      438652.583
#Sta/Elev= 30
       0  888.32    19.8  876.32    39.7  866.02    59.5  857.31    69.4   853.8
     119  841.25   148.8  835.79   158.7  833.34   218.2  813.98   257.9  798.62
   267.8  795.72   277.7  793.91   287.6  793.04   347.1  789.64   386.8  784.08
   406.6  782.18   415.6  782.36   426.5  783.96   430.6  785.22   446.3  789.25
   466.2  791.05     486  791.72   535.6  790.24   545.5  790.51   555.4  792.04
   565.3  795.82     605   815.8   664.5  844.61     734  877.06   813.3  915.34
#Mann= 3 , 0 , 0
       0     .06       0   415.6    .045       0   430.6     .06       0
Bank Sta=415.6,430.6
XS Rating Curve= 0 ,0
Exp/Cntr=0.3,0.1

Type RM Length L Ch R = 1 ,10821.5 ,352.3,354.2,356.2
XS GIS Cut Line= 3
     1889222.769      437770.544     1888984.185      438103.375
     1888747.714      438437.695
#Sta/Elev= 30
       0  917.12    59.9  881.91    99.9  862.21   129.8   849.2   209.8  818.77
   239.7  805.45   269.7  790.23   279.7  785.75   289.6  783.29   319.6  783.97
   339.6  783.26   379.6  779.39     402  776.05   409.5  775.68     417  776.51
   439.5  780.89   449.5  781.91   599.3  783.61   609.3  785.15   619.2  787.55
   629.2  790.99   649.2  799.58   659.2  804.54   669.2  809.81   679.2  816.15
   719.1  844.18   749.1  862.76   769.1  876.02     799  898.33     819  914.81
#Mann= 3 , 0 , 0
       0     .06       0     402    .045       0     417     .06       0
Bank Sta=402,417
XS Rating Curve= 0 ,0
Exp/Cntr=0.3,0.1

Type RM Length L Ch R = 1 ,10467.3 ,354.7,348.1,340.8
XS GIS Cut Line= 2
     1888985.607      437557.175     1888449.954      438183.908
#Sta/Elev= 30
       0  913.77    89.4  856.33   129.1  828.76   139.1  823.23   158.9  814.24
   188.7  802.78   208.6  796.35   238.4   788.7   268.2  779.98   278.1  777.93
     298  777.09   347.7   778.1   367.5  776.19   397.3  771.52   405.2  770.96
   407.3  770.81   420.2  771.91     447  775.17   526.5  778.89   536.4  780.38
   546.3   785.2   556.3  793.63   625.8  864.34   635.7  873.78   645.6  881.21
   655.6   886.3   665.5  889.96   695.3  899.16   725.1  909.84   824.4  950.32
#Mann= 3 , 0 , 0
       0      .1       0   405.2    .045       0   420.2      .1       0
#XS Ineff= 2 , 0
          338.16  778.24
Permanent Ineff=
       F       F
Bank Sta=405.2,420.2
XS Rating Curve= 0 ,0
Exp/Cntr=0.3,0.1

Type RM Length L Ch R = 1 ,10119.1 ,500.3,496.8,494
XS GIS Cut Line= 3
     1888578.886      437363.117     1888410.821      437742.968
     1888257.317      438125.761
#Sta/Elev= 30
       0  853.75    19.8  845.54    29.7  840.86   118.7  794.85   128.6  790.77
   138.5  788.34   148.4  787.65   158.2  787.85     178  789.85   187.9  790.33
   197.8  790.05   207.7  789.05   217.6  787.43   257.1  777.66     267  775.41
   276.9  773.87   326.4  773.27   405.5  766.58   413.8  766.29   415.4  766.24
   428.8  766.97   484.1  774.47   493.9  777.48     543  804.69   572.5  817.99
   582.3  822.01   621.6  835.71   719.8  871.97   768.9  891.25   827.8  915.42
#Mann= 3 , 0 , 0
       0      .1       0   413.8    .045       0   428.8      .1       0
Bank Sta=413.8,428.8
XS Rating Curve= 0 ,0
Exp/Cntr=0.3,0.1

Type RM Length L Ch R = 1 ,9621.9  ,269.7,271.7,272.8
XS GIS Cut Line= 3
     1888048.654      437256.372     1887892.512      437843.429
     1887920.207      438090.997
#Sta/Elev= 30
       0  863.39    19.9   851.7    99.6  807.01   139.4  783.27   149.4  778.58
   159.3  775.94   199.2  772.68   258.9  769.19   318.7  768.28   439.7   759.6
   448.1  759.19   454.7  759.45   458.1  759.58     478   763.8     488  765.34
   497.9   765.9   537.8  765.92   547.7  766.74   557.7  770.82   597.5  792.52
   627.4  807.04   637.4  811.55   647.3  815.13   657.3  818.06   687.2  826.12
   707.1  830.58   756.9  839.21   806.8  848.98   826.7  852.05   856.6  855.36
#Mann= 3 , 0 , 0
       0      .1       0   439.7    .045       0   454.7      .1       0
Bank Sta=439.7,454.7
XS Rating Curve= 0 ,0
Exp/Cntr=0.3,0.1

Type RM Length L Ch R = 1 ,9350.4  ,526.1,525.3,525.4
XS GIS Cut Line= 2
     1887806.366      437311.172     1887606.965      437849.065
#Sta/Elev= 30
       0  790.97    19.8  780.33    29.7  775.83    39.6   772.9    49.4  771.73
    98.9  769.33   128.6  767.05   187.9  764.85   197.8  763.75   207.7  760.72
   217.6  756.92   227.5  755.15   228.6  755.15   237.4  755.18   243.6  756.05
     267  759.74   286.8  761.14   415.4  763.41   435.2  764.18   445.1  765.51
   464.9  769.36   484.6  772.04   494.5  773.78   514.3  779.42   524.2  782.99
   534.1  787.68     544   793.9   553.9   801.6   563.8  810.11   573.7  818.12
#Mann= 3 , 0 , 0
       0      .1       0   228.6    .045       0   243.6      .1       0
Bank Sta=228.6,243.6
XS Rating Curve= 0 ,0
Exp/Cntr=0.3,0.1

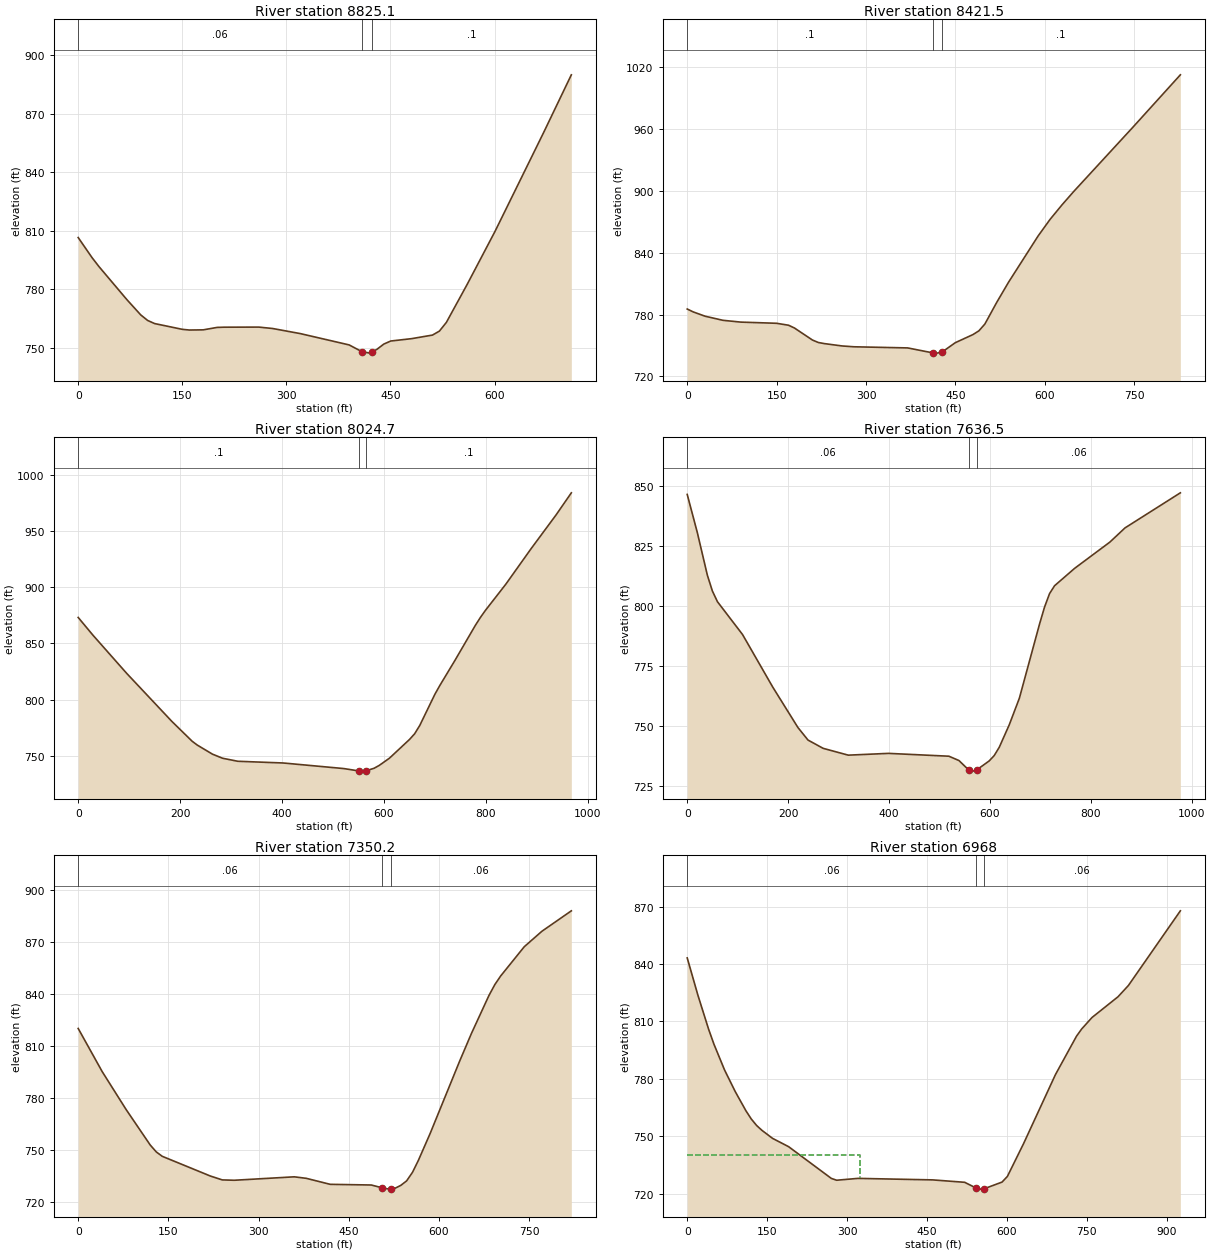
Type RM Length L Ch R = 1 ,8825.1  ,400.9,403.5,407.5
XS GIS Cut Line= 2
     1887346.443      437024.639     1887126.431      437700.366
#Sta/Elev= 30
       0  806.57      20  796.26      30  791.67    70.1   774.8    90.1  766.96
   100.1  764.11   110.1  762.52   150.1  759.56   160.1  759.21   180.2   759.3
   200.2  760.55   210.2  760.66   260.2  760.71   280.2  759.99   320.3  757.36
   390.4  751.59   408.6  748.18   420.4  747.38   423.6     748   430.4  749.31
   440.4  752.02   450.4  753.58   480.4  754.79   510.5  756.62   520.5  758.66
   530.5   763.1   560.5  782.58   600.5  809.63   670.6  860.29   710.6   889.9
#Mann= 3 , 0 , 0
       0     .06       0   408.6    .045       0   423.6      .1       0
Bank Sta=408.6,423.6
XS Rating Curve= 0 ,0
Exp/Cntr=0.3,0.1

Type RM Length L Ch R = 1 ,8421.5  ,406.3,396.5,385.3
XS GIS Cut Line= 3
     1887013.703      436913.313     1886838.595      437294.992
     1886646.469      437654.434
#Sta/Elev= 30
       0  785.36      10  782.57      30  778.39      60   774.4      90  772.66
     150  771.52     170  769.64     180  766.92     210  755.32     220  752.88
     230  751.82     260  749.52     280  748.72   369.9  747.62   412.4  742.78
   419.9  742.57   427.4  744.03   429.9  744.52   449.8  752.69   479.6   760.6
   489.5  764.23   499.5  770.82   519.3  791.76   539.2  811.37   588.9  856.31
   608.8  872.27   628.7  886.28   648.6  899.41     748  961.83   827.5 1012.58
#Mann= 3 , 0 , 0
       0      .1       0   412.4    .045       0   427.4      .1       0
Bank Sta=412.4,427.4
XS Rating Curve= 0 ,0
Exp/Cntr=0.3,0.1

Type RM Length L Ch R = 1 ,8024.7  ,392.3,388.2,384.3
XS GIS Cut Line= 3
     1886503.413       436646.62     1886500.337      436751.226
     1886498.798      437614.221
#Sta/Elev= 30
       0  873.08    28.5  857.54    95.1  823.37     184  780.52   223.7  762.93
   233.6  759.57   263.4   751.5   283.2  747.86     313  745.16   402.2  743.63
   521.3  738.66   550.2   736.6     561  736.39   565.2  736.72   580.8  738.98
   590.7  741.48   610.6  747.86   650.2   764.6   660.1  769.59   670.1  776.92
   699.8  804.68   709.7  812.67   739.5  835.08   779.2  865.99   789.1  873.01
     799  879.36   838.7  902.43   888.3  934.02   937.9  964.43   967.6  983.92
#Mann= 3 , 0 , 0
       0      .1       0   550.2    .045       0   565.2      .1       0
Bank Sta=550.2,565.2
XS Rating Curve= 0 ,0
Exp/Cntr=0.3,0.1

Type RM Length L Ch R = 1 ,7636.5  ,287.3,286.2,285.1
XS GIS Cut Line= 2
     1886015.767      436651.235     1886184.962      437614.205
#Sta/Elev= 30
       0  846.29      20  830.46    39.9  812.74    49.9  806.14    59.9   801.7
   109.7  788.04   169.6  766.18   219.5  749.38   239.4  744.18   269.4  740.73
   319.3  737.89   399.1  738.63   518.8  737.45   538.7  735.66     559  731.56
   568.7  731.25     574  731.77   598.6  735.48   608.6  737.71   618.6  741.15
   638.5  750.52   658.5  761.56   698.4  792.32   708.4  799.44   718.3  805.03
   728.3  808.33   768.2  815.58     838  826.48     868  832.38   977.7  846.96
#Mann= 3 , 0 , 0
       0     .06       0     559    .045       0     574     .06       0
Bank Sta=559,574
XS Rating Curve= 0 ,0
Exp/Cntr=0.3,0.1

Type RM Length L Ch R = 1 ,7350.2  ,379.2,382,384.9
XS GIS Cut Line= 3
     1885716.258      436752.726     1885809.181      437151.253
     1885899.846      437551.851
#Sta/Elev= 30
       0  820.13    39.9  795.31    79.8  773.43   119.8  753.06   129.8  749.12
   139.7  746.58   219.6  735.25   239.5     733   259.5  732.79   359.3  734.77
   379.3   733.9     419  730.45   487.4  730.06   504.4  728.54   516.8  727.69
   519.4  727.81   526.6  728.14   536.4  729.84   546.1  732.43   555.9  737.37
   565.7  744.26   585.2  759.68   634.1  801.18   653.7  817.11     683  839.11
   692.8  845.38   702.6  850.38   741.7  867.15     771  876.04     820  887.82
#Mann= 3 , 0 , 0
       0     .06       0   504.4    .045       0   519.4     .06       0
Bank Sta=504.4,519.4
XS Rating Curve= 0 ,0
Exp/Cntr=0.3,0.1

Type RM Length L Ch R = 1 ,6968    ,573.2,587.9,602.5
XS GIS Cut Line= 3
     1885401.979      436755.841     1885471.204      437463.466
     1885486.587      437677.291
#Sta/Elev= 30
       0  843.25      20  823.79    40.1  805.99    50.1  798.16    70.1  784.61
    90.1  773.34   110.2  763.28   120.2     759   130.2  755.61   140.2  753.06
   160.2  748.85   190.3  744.51   270.4  727.92   280.4  726.96   320.4  727.93
   460.6  727.14   520.7  725.88   542.2  722.86   550.8  722.31   557.2  722.51
   590.8     726   600.8  728.95   630.9  745.95     691  782.22   730.5   802.3
   740.2  806.08   759.7   812.1   808.4  822.93   827.9  828.82   925.4  867.88
#Mann= 3 , 0 , 0
       0     .06       0   542.2    .045       0   557.2     .06       0
#XS Ineff= 2 , 0
          323.42  740.06
Permanent Ineff=
       F       F
Bank Sta=542.2,557.2
XS Rating Curve= 0 ,0
Exp/Cntr=0.3,0.1

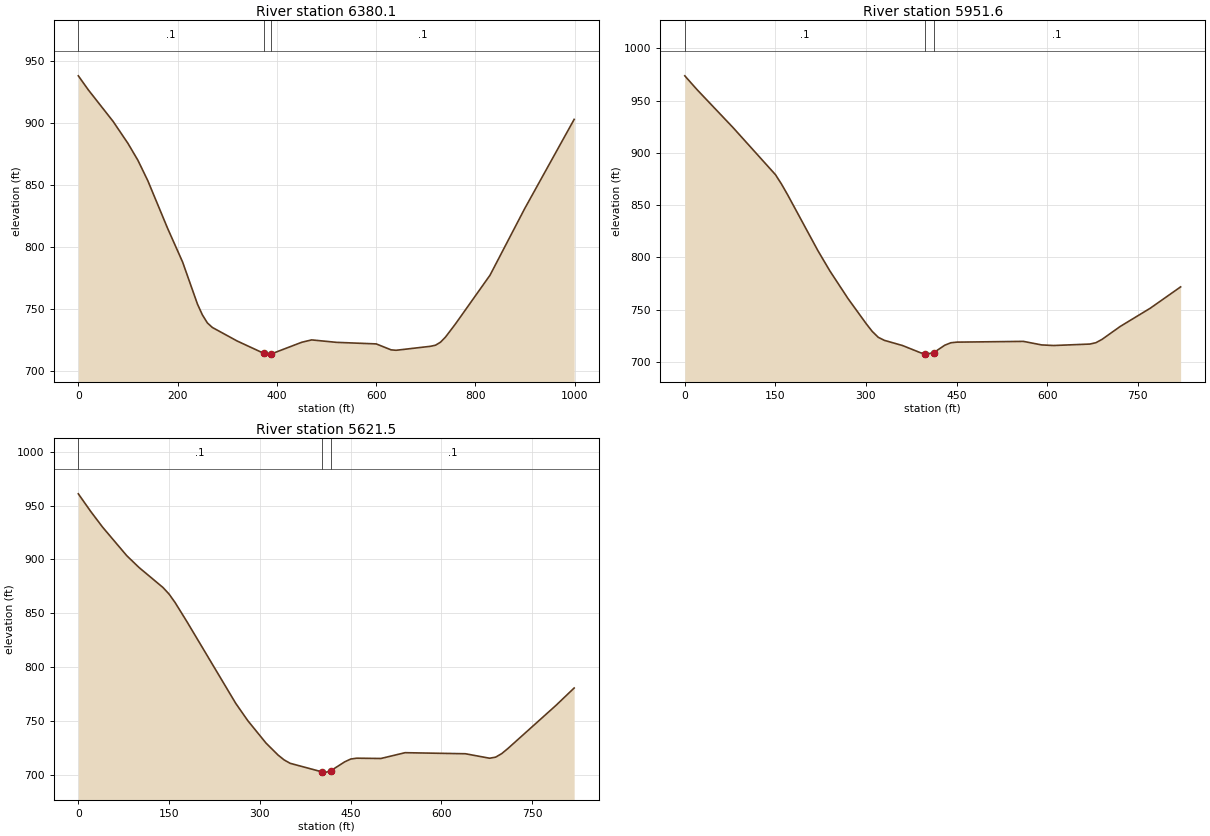
Type RM Length L Ch R = 1 ,6380.1  ,437.3,428.5,419.7
XS GIS Cut Line= 4
     1885043.552      436695.846     1885009.229       437044.09
     1884870.877      437264.515     1884847.956      437652.553
#Sta/Elev= 30
       0  938.07      20  926.81      70  901.35     100  883.56     120  869.98
     140  853.48     180  814.93     210  787.97     240  753.98     250  745.23
     260  738.76     270  735.13   319.9  724.22   373.7  714.24     380  713.62
   388.7  713.78     450  723.17     470  725.09   520.1  723.12   600.2  721.86
   630.1  717.06   640.1  716.72   709.8  719.95   719.8  720.85   729.8  723.29
   739.8  727.43   759.7  737.93   829.4  777.29   899.2  830.95   998.9  902.94
#Mann= 3 , 0 , 0
       0      .1       0   373.7    .045       0   388.7      .1       0
#XS Ineff= 2 , 0
                          469.78             725
Permanent Ineff=
       F       F
Bank Sta=373.7,388.7
XS Rating Curve= 0 ,0
Exp/Cntr=0.3,0.1

Type RM Length L Ch R = 1 ,5951.6  ,327.4,330,332.9
XS GIS Cut Line= 2
     1884659.562      436636.353     1884526.609       437446.66
#Sta/Elev= 30
       0  973.61      20  960.58    80.1  924.02   150.2  879.09   160.2  870.08
   170.2  860.01   220.3  806.63   240.3  787.08   270.4  760.61   300.4  736.69
   310.4  729.31   320.4  723.66   330.5  720.76   360.5  715.82   390.5  708.88
   397.4     708   400.6  707.59   412.4  709.07   430.6  716.14   440.6  718.44
   450.6  719.05   560.8  719.77   590.8   716.4   610.8  715.82   670.9  717.21
     681  718.55     691  721.71     721  734.01   771.1  751.58   821.1  771.87
#Mann= 3 , 0 , 0
       0      .1       0   397.4    .045       0   412.4      .1       0
Bank Sta=397.4,412.4
XS Rating Curve= 0 ,0
Exp/Cntr=0.3,0.1

Type RM Length L Ch R = 1 ,5621.5  ,391.3,399.7,406.3
XS GIS Cut Line= 3
     1884379.237        436598.4     1884267.526      436993.173
     1884148.707      437384.865
#Sta/Elev= 30
       0  960.88      20   944.9      40  930.03      80  903.51   100.1  892.63
   140.1  873.86   150.1  867.76   160.1  859.87   180.1  841.71   260.2  766.43
   280.2  750.33   310.2  729.59   330.2  718.44   340.2  713.94   350.2  710.78
   402.8  702.84   410.3  702.61   417.8  704.06   440.2  712.12   450.2  714.75
   460.2  715.54   500.1  715.26   540.1  720.65   639.9  719.66   679.8  715.51
   689.8  716.51   699.8  719.77   709.8  724.39   789.6  764.58   819.6  780.67
#Mann= 3 , 0 , 0
       0      .1       0   402.8    .045       0   417.8      .1       0
Bank Sta=402.8,417.8
XS Rating Curve= 0 ,0
Exp/Cntr=0.3,0.1