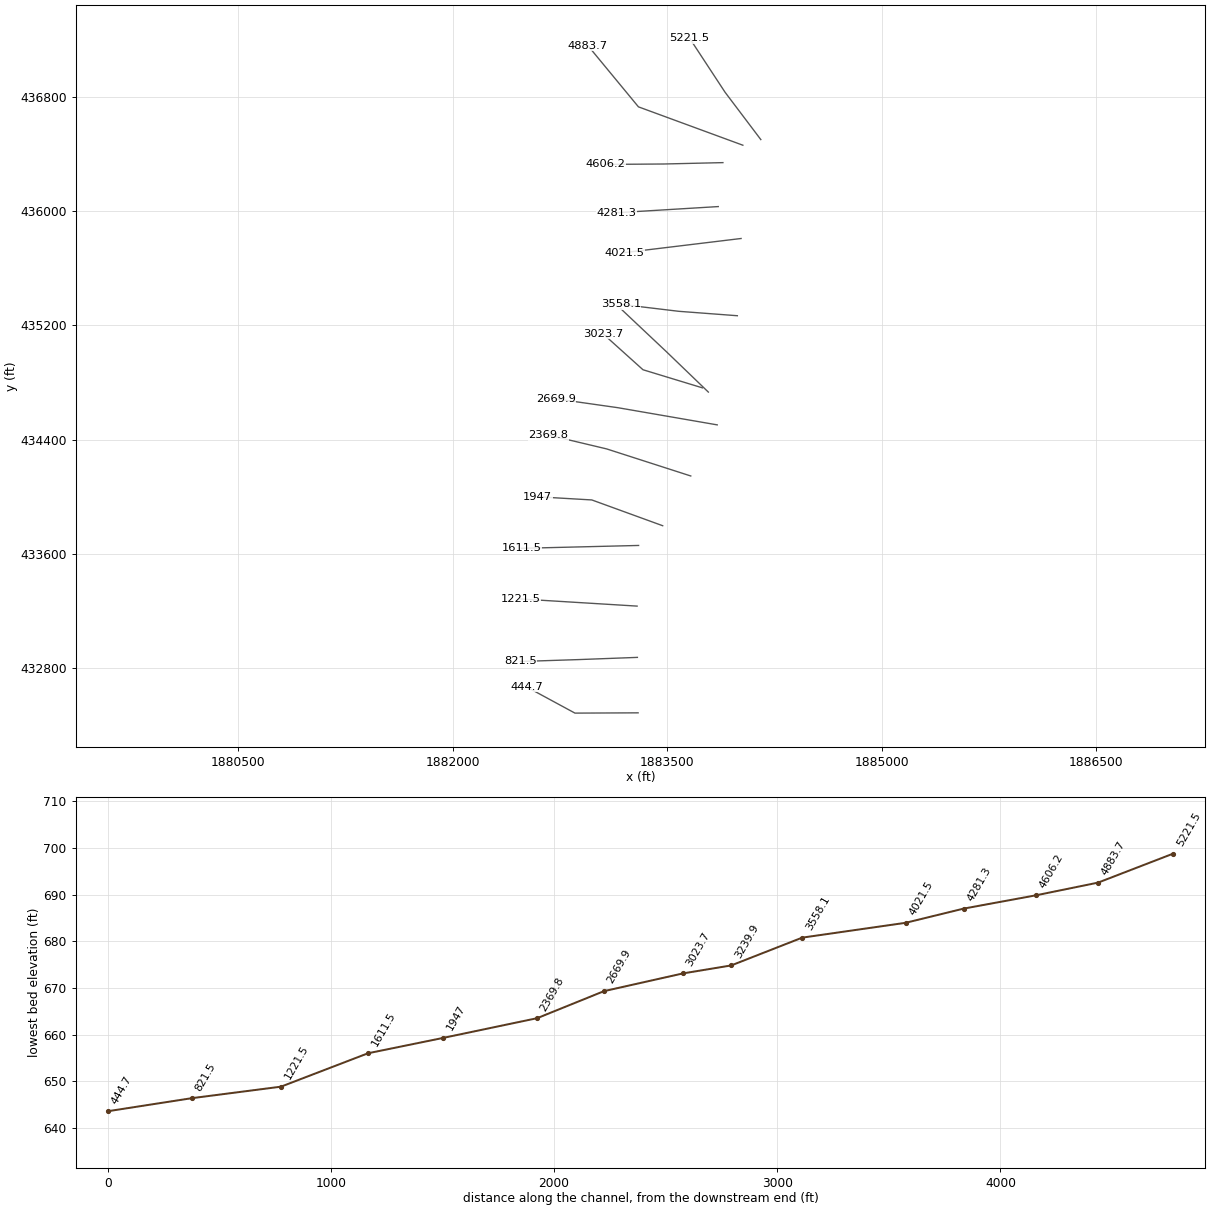
HEC-RAS study SmithersCk.prj: SmithersCk

--- SmithersCk.g01 (geometry) --- (continued)

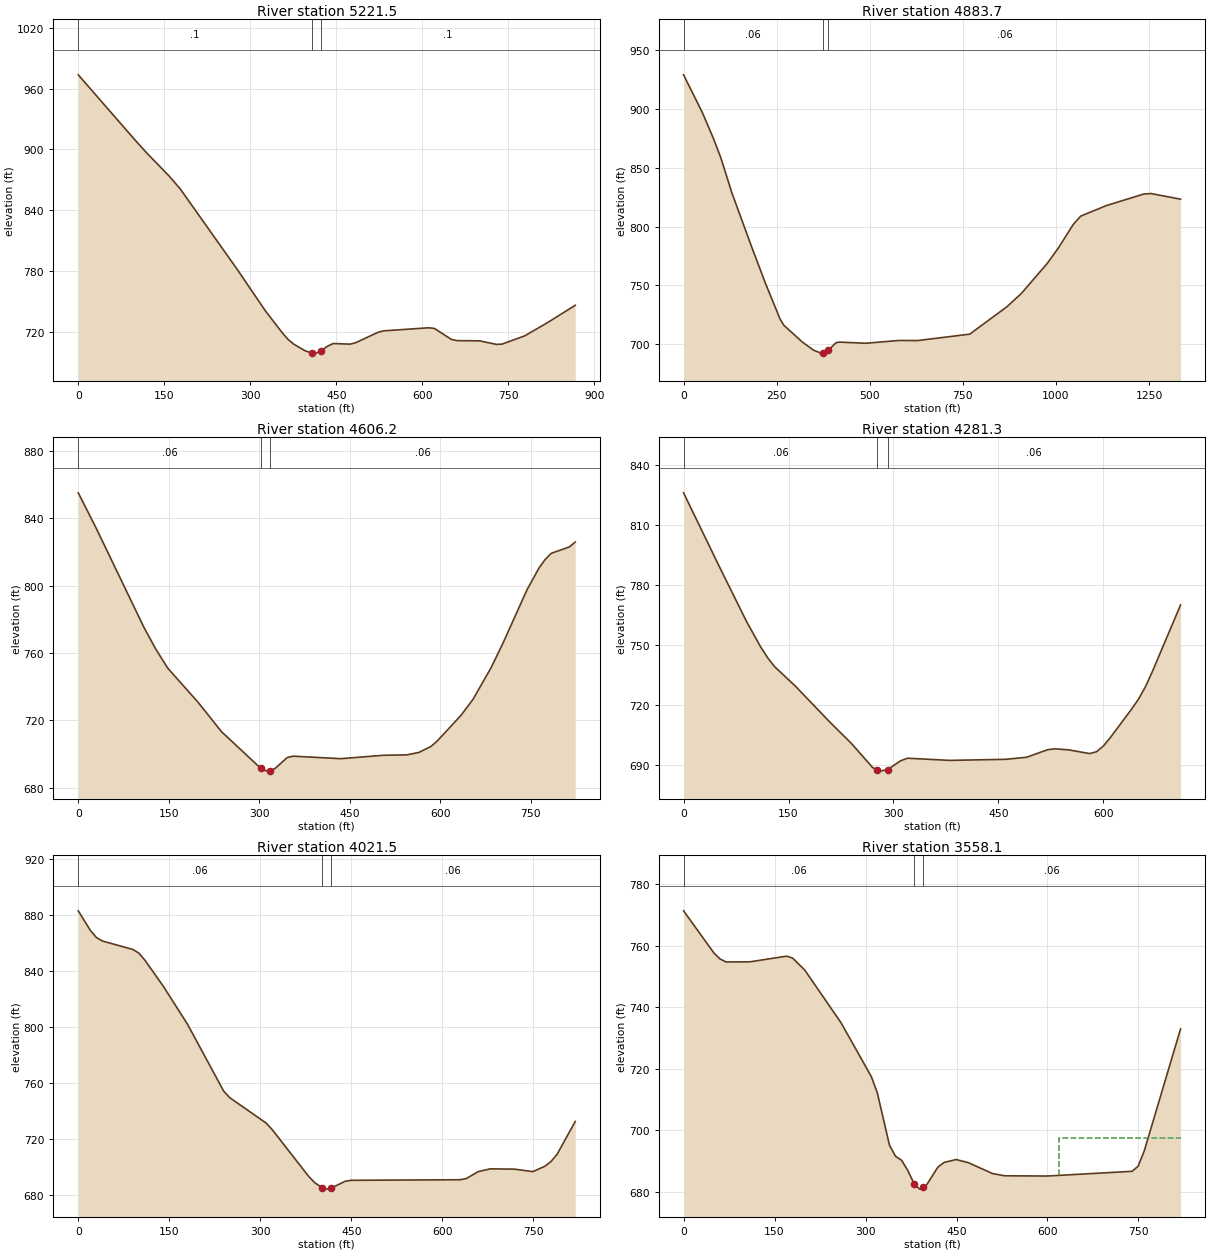
Type RM Length L Ch R = 1 ,5221.5  ,324.9,337.9,352.4
XS GIS Cut Line= 3
     1884155.144      436500.479     1883905.164      436831.805
      1883657.53      437209.644
#Sta/Elev= 30
       0   973.5    98.8  909.31   118.6   896.9   158.1  873.84   177.9  860.89
   276.7  781.93   326.1  740.78   355.8  718.92   365.6  712.51   375.5  707.83
   395.3  701.24   407.6  698.94     415  698.83   422.6  700.89   434.7  705.62
   444.5   708.3     474  707.69   483.8   709.1   523.1  719.45   532.9  720.82
   611.5  723.87   621.3  723.16   650.8  712.37   660.6  711.16   699.8  710.95
   729.3  707.47   739.1  707.71   778.4  715.83   817.7  728.68   866.8  746.06
#Mann= 3 , 0 , 0
       0      .1       0   407.6    .045       0   422.6      .1       0
Bank Sta=407.6,422.6
XS Rating Curve= 0 ,0
Exp/Cntr=0.3,0.1

Type RM Length L Ch R = 1 ,4883.7  ,268.6,277.2,285.9
XS GIS Cut Line= 3
     1884029.519       436461.05     1883299.102      436729.689
      1882945.29      437158.879
#Sta/Elev= 30
       0  928.76    49.9  897.09    79.8   875.1    99.8  858.58   129.7  828.65
   179.6  785.47   219.5  752.12   259.4  721.31   269.4  716.17   319.3  701.91
   349.2  695.07   369.2  692.59   373.5  692.67   388.5  694.94   409.1  701.41
   419.1  701.95   488.9  700.96   578.7  703.34   628.6  703.25   768.3  708.69
   867.6  731.79   907.4  743.35   976.9  768.87  1006.7  781.96  1046.4  801.79
  1066.3  808.85  1135.8  817.86  1235.2  827.54    1255  828.01  1334.5  823.24
#Mann= 3 , 0 , 0
       0     .06       0   373.5    .045       0   388.5     .06       0
Bank Sta=373.5,388.5
XS Rating Curve= 0 ,0
Exp/Cntr=0.3,0.1

Type RM Length L Ch R = 1 ,4606.2  ,324.4,324.9,325.4
XS GIS Cut Line= 3
     1883889.989      436339.113     1883474.503      436329.477
      1883066.09      436326.539
#Sta/Elev= 30
       0  855.09    29.7   834.1   108.8  775.27   128.6  762.28   148.4  750.99
   197.9  731.08   237.5  713.29   302.9  691.45   306.8  690.44   316.6  689.88
   317.9  690.09   326.5   691.5   346.3  697.91   356.2  698.76   435.5  697.27
   505.2  699.27   545.1  699.55     565  701.01   584.9  704.57   594.9  707.66
   634.8  723.08   654.7  732.62   684.6  751.38   704.5  766.12   744.3  797.76
   764.2   810.6   774.2  815.56   784.2  819.18   814.1  822.96     824  825.87
#Mann= 3 , 0 , 0
       0     .06       0   302.9    .045       0   317.9     .06       0
Bank Sta=302.9,317.9
XS Rating Curve= 0 ,0
Exp/Cntr=0.3,0.1

Type RM Length L Ch R = 1 ,4281.3  ,258.3,259.8,261.2
XS GIS Cut Line= 2
     1883857.511      436031.294     1883148.347      435988.221
#Sta/Elev= 30
       0  825.96      50  789.92    90.1  761.67   110.1  749.09   120.1  743.67
   130.1  739.19   160.1  729.36   210.1  711.16   240.2  700.75   270.2  688.84
   276.6  687.68   280.2  687.02   291.6  687.75   310.2  692.17   320.2  693.47
   380.2  692.38   460.3  692.91   490.3  693.93   520.3   697.7   530.4  698.16
   550.4  697.65   580.4  695.79   590.4  696.69   600.4  699.65   610.4  703.91
   640.4  717.93   650.4  722.98   660.4  729.22   670.4   736.9   710.5  769.98
#Mann= 3 , 0 , 0
       0     .06       0   276.6    .045       0   291.6     .06       0
Bank Sta=276.6,291.6
XS Rating Curve= 0 ,0
Exp/Cntr=0.3,0.1

Type RM Length L Ch R = 1 ,4021.5  ,467.8,463.4,459
XS GIS Cut Line= 3
     1884017.064      435807.744      1883610.54      435758.468
     1883204.015      435709.191
#Sta/Elev= 30
       0  883.01      20  868.97      30  863.88      40  861.38    89.9  855.39
    99.9  852.76   109.9  847.66   139.8   829.3   179.8  802.08   239.7  754.05
   249.7  749.35   309.6  731.24   319.6  726.56   379.5   693.2   389.5  688.65
     402  684.92   409.5  683.98     417  684.77   439.5  689.53   449.4  690.29
   629.2  690.69   639.2  691.48   659.2  696.54   679.2  698.49   719.1  698.26
   749.1   696.5   769.1  700.36     779  703.72     789  708.84     819  732.37
#Mann= 3 , 0 , 0
       0     .06       0     402    .045       0     417     .06       0
Bank Sta=402,417
XS Rating Curve= 0 ,0
Exp/Cntr=0.3,0.1

Type RM Length L Ch R = 1 ,3558.1  ,333.7,318.2,302.8
XS GIS Cut Line= 3
      1883990.93      435266.859     1883582.676      435297.672
     1883175.609       435346.46
#Sta/Elev= 30
       0  771.31    49.9  757.64    59.9  755.69    69.9  754.68   109.8  754.73
   169.8  756.57   179.7  755.96   199.7  752.08   259.6  734.92   309.6  717.38
   319.5  712.06   339.5  695.08   349.5  691.47   359.5  690.16   369.5  686.93
   380.3  682.48   389.4   680.8   395.3  681.38   399.4  681.79   419.4  687.98
   429.4  689.47   449.4  690.42   469.4  689.42   509.4  685.86   529.4  685.14
   599.4  685.06   739.4  686.59   749.4  688.23   759.4  693.16   819.4   732.9
#Mann= 3 , 0 , 0
       0     .06       0   380.3    .045       0   395.3     .06       0
#XS Ineff= 2 , 0
                          619.05          697.57
Permanent Ineff=
       F       F
Bank Sta=380.3,395.3
XS Rating Curve= 0 ,0
Exp/Cntr=0.3,0.1

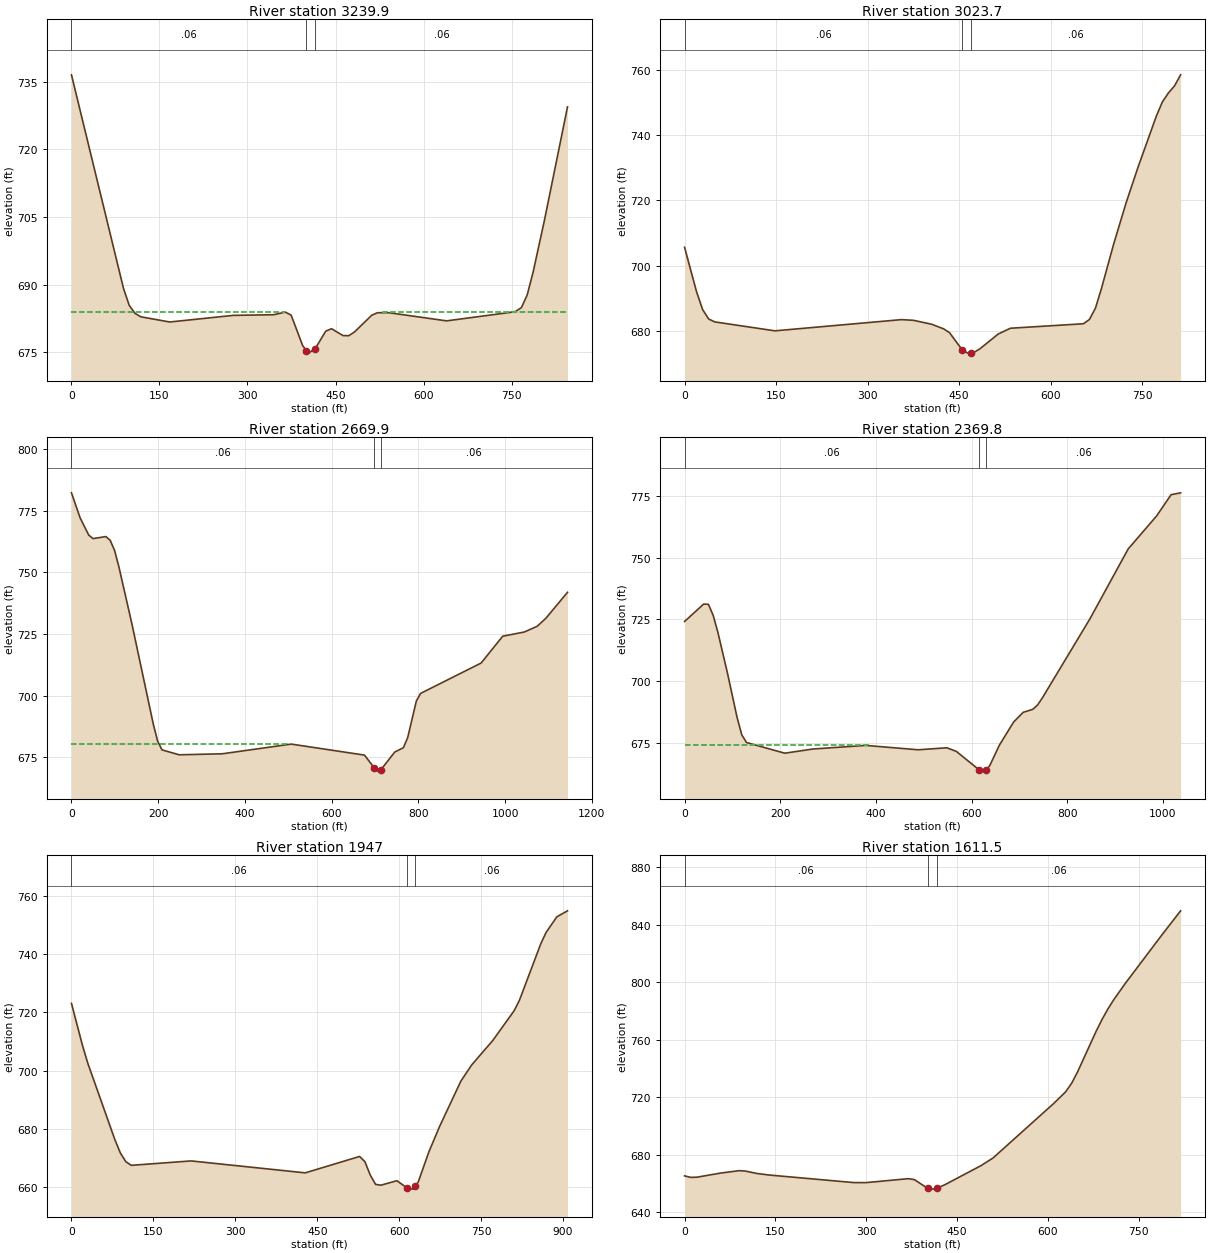
Type RM Length L Ch R = 1 ,3239.9  ,214.1,216.1,217.8
XS GIS Cut Line= 3
     1883788.076      434732.138     1883497.233       435012.46
     1883176.121      435315.355
#Sta/Elev= 30
       0  736.52    88.7  689.17    98.5  685.41   108.4  683.64   118.2  682.89
   167.5  681.74   275.9  683.21   344.8  683.35   364.5  683.93   374.4  683.26
   394.1  676.48   400.5  675.41   403.9  674.84   415.5  675.84   433.4  679.72
   443.2  680.25   462.8  678.73   472.6   678.7   482.4  679.53   511.8  683.24
   521.7   683.8   541.3  683.79   639.4  681.99   747.3  683.86   757.1  684.09
   766.9  684.94   776.7  687.74   786.5  692.64   806.1   704.3   845.4  729.43
#Mann= 3 , 0 , 0
       0     .06       0   400.5    .045       0   415.5     .06       0
#XS Ineff= 2 , 0
          364.53  683.93  531.56          683.95
Permanent Ineff=
       F       F
Bank Sta=400.5,415.5
XS Rating Curve= 0 ,0
Exp/Cntr=0.3,0.1

Type RM Length L Ch R = 1 ,3023.7  ,342.3,353.8,366.1
XS GIS Cut Line= 3
      1883746.34      434761.824     1883330.923      434888.511
     1883049.559      435141.886
#Sta/Elev= 30
       0  705.62    19.7  691.95    29.6   686.5    39.5  683.61    49.4  682.72
   148.1  679.97   355.3  683.41   375.1   683.2   404.7  682.01   424.4   680.6
   434.3  679.39   454.8  674.18   464.2  673.13   469.8  673.25   474.2  673.34
   484.1  674.47     514  678.99     534  680.77   653.5  682.14   663.5  683.45
   673.4  686.96   683.4  693.12   703.3  706.67   723.3  719.08   743.2  730.23
   773.1  745.86     783  750.21     793     753     803  755.16   812.9  758.54
#Mann= 3 , 0 , 0
       0     .06       0   454.8    .045       0   469.8     .06       0
#XS Ineff= 2 , 0
          355.24   683.4
Permanent Ineff=
       F       F
Bank Sta=454.8,469.8
XS Rating Curve= 0 ,0
Exp/Cntr=0.3,0.1

Type RM Length L Ch R = 1 ,2669.9  ,302.6,299.8,297.8
XS GIS Cut Line= 3
     1883850.292      434502.418     1883155.123      434622.766
     1882721.236      434684.524
#Sta/Elev= 30
       0  782.34    19.9   772.2    39.8  765.19    49.7  763.75    79.5  764.58
    89.4  763.02    99.4  758.95   109.3  752.33   139.1  729.33   188.8  688.33
   198.7  681.52   208.7  677.96   248.4  675.96   347.8  676.37   506.8  680.31
   675.7  675.83   698.7  670.53   705.5  669.33   713.7  669.94   745.4  677.07
   765.3  678.84   775.2  682.89   795.2  697.77   805.1   700.9   944.6  713.22
   994.4  724.12  1044.2  725.82    1074  728.16    1094  731.42  1143.8  741.95
#Mann= 3 , 0 , 0
       0     .06       0   698.7    .045       0   713.7     .06       0
#XS Ineff= 2 , 0
          496.53  680.33
Permanent Ineff=
       F       F
Bank Sta=698.7,713.7
XS Rating Curve= 0 ,0
Exp/Cntr=0.3,0.1

Type RM Length L Ch R = 1 ,2369.8  ,416.9,422.3,426.3
XS GIS Cut Line= 3
     1883665.019       434144.54     1883076.644      434334.104
     1882668.979      434431.159
#Sta/Elev= 30
       0  724.18    39.9  731.24    49.8  731.15    59.8  726.71    69.8   719.7
    89.7  703.25   109.7  685.41   119.6  678.23   129.6  675.12   209.4   670.8
   269.2  672.51   378.9  673.95   488.5  672.18   548.4  672.99   568.3  671.53
   615.7  664.09   628.1  663.53   630.7   664.1   638.1  665.74   658.1     674
     688  683.42     708  687.36   727.9  688.56   737.9  690.28   747.9  693.13
   847.6  725.26   927.5  753.56   987.3  767.03  1017.3  775.58  1037.2  776.33
#Mann= 3 , 0 , 0
       0     .06       0   615.7    .045       0   630.7     .06       0
#XS Ineff= 2 , 0
          388.61  673.93
Permanent Ineff=
       F       F
Bank Sta=615.7,630.7
XS Rating Curve= 0 ,0
Exp/Cntr=0.3,0.1

Type RM Length L Ch R = 1 ,1947    ,333.6,335.4,337.3
XS GIS Cut Line= 3
     1883468.661      433796.164     1882973.017      433976.686
      1882592.97      433998.856
#Sta/Elev= 30
       0   723.1    19.9  708.84    29.9  702.53    79.6  676.22    89.6  671.68
    99.5  668.72   109.5  667.46     219  668.98     428  664.88   527.5  670.51
   537.3   668.7     547  664.15   556.8  660.93   566.5  660.64   595.8  662.18
   614.5  659.69   625.1  659.29   629.5  660.39   634.9  661.75   654.4   672.1
   673.9  680.77     713  696.41   732.5  701.88   771.5  710.38   810.6   720.6
   820.3  724.22   859.4  743.63   869.1  747.51   888.7  752.83   908.2  754.88
#Mann= 3 , 0 , 0
       0     .06       0   614.5    .045       0   629.5     .06       0
Bank Sta=614.5,629.5
XS Rating Curve= 0 ,0
Exp/Cntr=0.3,0.1

Type RM Length L Ch R = 1 ,1611.5  ,391.9,390,388.1
XS GIS Cut Line= 2
     1883300.187      433657.953     1882481.188      433637.903
#Sta/Elev= 30
       0  665.24      10  664.21      20   664.3    59.9  667.21    89.9  668.86
    99.9  668.64   119.9  666.88   139.9  665.82   279.7  660.56   299.7  660.54
   369.7   663.3   379.6  662.64   399.6  657.08     402  656.82   409.6  656.01
     417  656.68   429.6  659.02   489.6  672.38   509.5  677.73   609.4  715.57
   629.4   723.8   639.4  729.83   649.4  737.97   679.4  765.68   689.4  774.15
   699.4  781.67   709.4   788.3   729.3   800.1   789.3   833.6   819.2  849.82
#Mann= 3 , 0 , 0
       0     .06       0     402    .045       0     417     .06       0
Bank Sta=402,417
XS Rating Curve= 0 ,0
Exp/Cntr=0.3,0.1

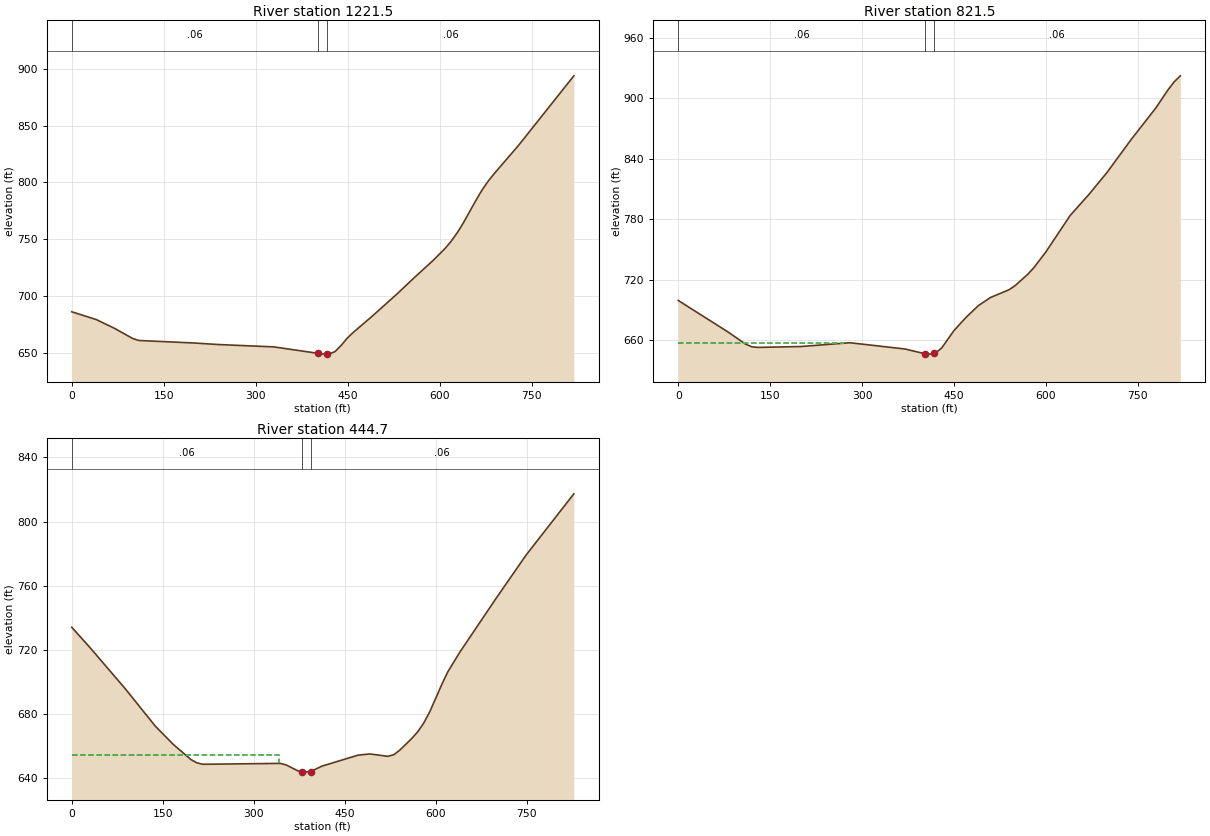
Type RM Length L Ch R = 1 ,1221.5  ,397.8,400,402.1
XS GIS Cut Line= 3
     1883289.865      433233.165     1882881.131       433258.19
     1882472.396      433283.214
#Sta/Elev= 30
       0   686.1      40  679.25    69.9  671.49    99.9  662.46   109.9  660.84
   199.8  658.64   239.7  657.28   329.6  655.21     402  649.52   409.5  648.92
     417  648.87   419.5  648.85   429.5  651.11   439.5  656.56   449.4  662.92
   459.4  668.05   489.4   681.9   529.4  701.22   559.3  716.44   589.3  731.24
   609.3  742.05   619.2   748.4   629.2  755.96   639.2  764.72   659.2  784.09
   669.2  793.18   679.2     801   689.2  807.73   729.1  832.72     819  893.72
#Mann= 3 , 0 , 0
       0     .06       0     402    .045       0     417     .06       0
Bank Sta=402,417
XS Rating Curve= 0 ,0
Exp/Cntr=0.3,0.1

Type RM Length L Ch R = 1 ,821.5   ,377.4,376.6,375.9
XS GIS Cut Line= 3
     1883291.712      432874.062     1882882.112      432858.677
     1882473.112      432845.287
#Sta/Elev= 30
       0  699.56      80  668.81     110  656.26     120  653.66     130  653.05
     200  653.91   279.9  657.67   369.9  651.48   402.4  646.78   409.9  646.38
   417.4  647.18   419.9  647.44   429.8  652.45   449.8   669.7   469.8  682.98
   489.7  694.44   509.7  702.59   539.6  710.16   549.6  714.28   569.6  725.13
   579.6  731.64   599.5  747.41   639.4  783.79   669.4  804.18   699.3  826.25
   739.3  859.39   779.2  890.35   799.2  908.44   809.1  916.23   819.1  922.19
#Mann= 3 , 0 , 0
       0     .06       0   402.4    .045       0   417.4     .06       0
#XS Ineff= 2 , 0
          269.75  657.85
Permanent Ineff=
       F       F
Bank Sta=402.4,417.4
XS Rating Curve= 0 ,0
Exp/Cntr=0.3,0.1

Type RM Length L Ch R = 1 ,444.7   ,475.4,444.5,413.6
XS GIS Cut Line= 3
     1883296.774      432485.695     1882854.963       432483.75
      1882515.92      432667.468
#Sta/Elev= 30
       0  733.99    29.4  721.62    88.4  695.52   137.4  672.41   166.9  661.04
   196.4  651.42   206.2  649.38     216  648.48   343.6  649.04   353.4  648.07
   373.1  644.27   378.6  643.88   382.9  643.58   393.6  643.97   412.4  647.33
   471.5  654.15   491.2  654.94   520.9  653.43   530.8  654.46   540.7  657.36
   560.5  664.66   570.4   668.9   580.2  674.35   590.1  681.34   609.9  698.42
   619.8  706.25   639.6  718.52   698.9  751.87   748.3  778.88   827.4  817.32
#Mann= 3 , 0 , 0
       0     .06       0   378.6    .045       0   393.6     .06       0
#XS Ineff= 2 , 0
          341.72  654.54
Permanent Ineff=
       F       F
Bank Sta=378.6,393.6
XS Rating Curve= 0 ,0
Exp/Cntr=0.3,0.1

Chan Stop Cuts=-1
Use User Specified Reach Order=0
Composite Channel Slope=5